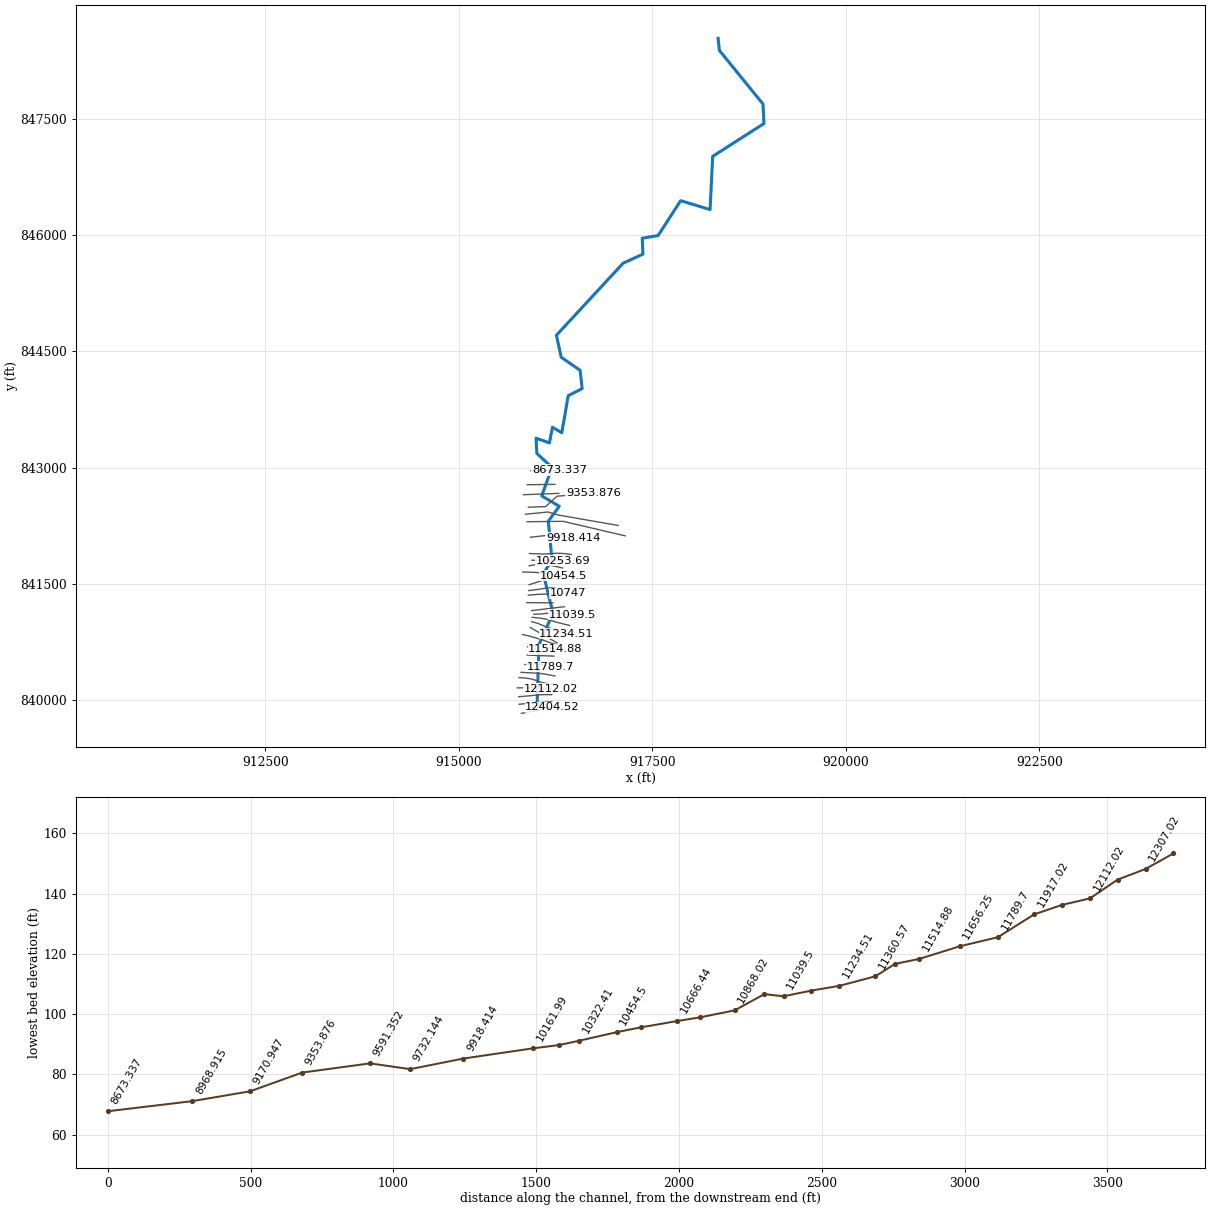
--- 16794_ras.prj (project) ---

Proj Title=16794
Current Plan=p01
Default Exp/Contr=0.3,0.1
English Units
Geom File=g01
Flow File=f01
Plan File=p01
Y Axis Title=Elevation
X Axis Title(PF)=Main Channel Distance
X Axis Title(XS)=Station
BEGIN DESCRIPTION:
RFD model 16794 exported to HEC-RAS
END DESCRIPTION:

--- 16794_ras.p01 (plan) ---

Plan Title=Plan 01
Program Version=4.10
Short Identifier=Plan 01
Geom File=g01
Flow File=f01
Subcritical Flow
Calc Critical at every XS
Secant Critical Depth

--- 16794_ras.f01 (steady flow) ---

Flow Title=Flow 01
Program Version=5.01
Number of Profiles= 6
Profile Names=10yr,25yr,50yr,100yr,100plus,500yr
River Rch & RM=16794,48,12404.52
  216.24  341.48  457.13  560.85  818.85 1355.47
River Rch & RM=16794,48,12307.02
  223.45  353.15  473.02  580.62  847.71 1397.82
River Rch & RM=16794,48,12209.52
  227.26   359.3  481.39  591.01  862.88 1419.91
River Rch & RM=16794,48,12112.02
  231.02  365.39  489.68  601.33  877.94 1441.86
River Rch & RM=16794,48,12014.52
  236.36  373.99  501.36  615.82  899.09 1472.37
River Rch & RM=16794,48, 11789.7
  242.77  384.35  515.43  633.28  924.59  1509.1
River Rch & RM=16794,48,11656.25
  248.35  393.36   527.7  648.55  946.88 1541.21
River Rch & RM=16794,48,11514.88
  250.15  396.31  531.73  653.57  954.21 1551.86
River Rch & RM=16794,48,11429.51
  253.33  401.51  538.87  662.52  967.27 1570.95
River Rch & RM=16794,48,11234.51
  255.78  405.54  544.41  669.45   977.4 1585.74
River Rch & RM=16794,48,11137.01
  269.31   427.6  574.59  707.15 1032.43 1665.09
River Rch & RM=16794,48, 11039.5
  270.01  428.75  576.16  709.11  1035.3 1669.22
River Rch & RM=16794,48,10971.86
  275.84  438.34  589.35  725.65 1059.46 1704.21
River Rch & RM=16794,48,   10747
  277.91  441.73     594  731.49 1067.97 1716.49
River Rch & RM=16794,48,10666.44
  280.29  445.65  599.39  738.26 1077.85 1730.77
River Rch & RM=16794,48,10540.64
  286.53  455.85  613.38  755.75 1103.39 1767.29
River Rch & RM=16794,48, 10454.5
  290.57  462.51  622.54  767.25 1120.19 1791.47
River Rch & RM=16794,48,10322.41
  294.99  469.76   632.5  779.74 1138.42 1817.52
River Rch & RM=16794,48,10253.69
  297.95  474.66  639.27  788.26 1150.86 1835.48
River Rch & RM=16794,48,9918.414
  304.96   486.2  655.15   808.2 1179.97  1877.1
River Rch & RM=16794,48,9732.144
  309.02  493.01  664.63  820.22 1197.52 1902.68
River Rch & RM=16794,48,9353.876
  309.96  494.59  666.82  822.99 1201.57 1908.57
River Rch & RM=16794,48,9170.947
  330.32  528.28  713.35  881.59 1287.12 2030.56
River Rch & RM=16794,48,8968.915
  336.09  537.97  726.87  898.76 1312.18 2066.79
River Rch & RM=16794,48,8673.337
  469.54  761.07 1037.06 1291.63 1885.79 2867.02
River Rch & RM=16794,48,8290.941
  477.28  773.98    1055 1314.34 1918.93    2912
River Rch & RM=16794,48,7925.288
  482.13  782.08 1066.25 1328.59 1939.74 2940.18
River Rch & RM=16794,48,7724.031
  487.99  791.92 1079.98 1346.02 1965.18 2974.84
River Rch & RM=16794,48, 7446.68
  490.46  796.09 1085.81 1353.43 1976.01 2989.65
River Rch & RM=16794,48,7284.188
  494.26  802.51  1094.8  1364.9 1992.75 3012.62
River Rch & RM=16794,48,7088.748
   497.5  807.99 1102.49 1374.71 2007.07 3032.26
River Rch & RM=16794,48,6707.842
  524.25   853.3 1166.03 1455.77 2125.43 3194.03
River Rch & RM=16794,48,6569.536
  526.65  857.36 1171.72 1463.03 2136.02 3208.44
River Rch & RM=16794,48,6264.719
  535.39  872.16 1192.48 1489.53 2174.71 3261.02
River Rch & RM=16794,48,5965.187
  538.85  878.01 1200.67 1499.97 2189.95 3281.65
River Rch & RM=16794,48, 5777.56
  539.65  879.36 1202.56 1502.38 2193.47  3286.4
River Rch & RM=16794,48,5537.232
  545.97  890.07 1217.58 1521.55 2221.46 3324.32
River Rch & RM=16794,48,5349.975
  547.54  892.73 1221.33 1526.33 2228.44 3333.77
Boundary for River Rch & Prof#=16794,48,1
Up Type= 0
Dn Type= 2
Boundary for River Rch & Prof#=16794,48,2
Up Type= 0
Dn Type= 2
Boundary for River Rch & Prof#=16794,48,2
Up Type= 0
Dn Type= 2
Boundary for River Rch & Prof#=16794,48,2
Up Type= 0
Dn Type= 2
Boundary for River Rch & Prof#=16794,48,2
Up Type= 0
Dn Type= 2
Boundary for River Rch & Prof#=16794,48,2
Up Type= 0
Dn Type= 2

--- 16794_ras.g01 (geometry) ---

Geom Title=16794
Program Version=4.10

River Reach=16794,48
Reach XY= 30
916009.082842991839867.072043367916036.123285991840714.234800719
916217.228843157841121.792836733916090.600100529841627.448545729
916203.907763199 841804.45862815916156.338366764842307.322659801
916298.170368631842500.413155786 916071.09683372842633.681875029
916203.778622466843003.286936819916008.637392619843181.171019392
915997.902554053843380.246129068916170.700638174 843319.54217147
916209.908861604843521.320054914916330.810574685843449.985796351
916413.736682568843929.096915655916593.614864781 844020.55296256
916567.024864719844256.139832041916322.421368529844425.511742604
916261.368743505844709.583769598917121.927112164845638.987007879
917378.661008864845756.989295377917369.608178162845962.033245802
917574.921619682845997.713782364917865.783066124846447.344355093
918245.643891215846331.899277455 918279.26280111847019.705272147
918941.732844464847442.979260735918929.378848895847694.777911534
918365.868890077848387.635802216918349.097680417848543.701567123

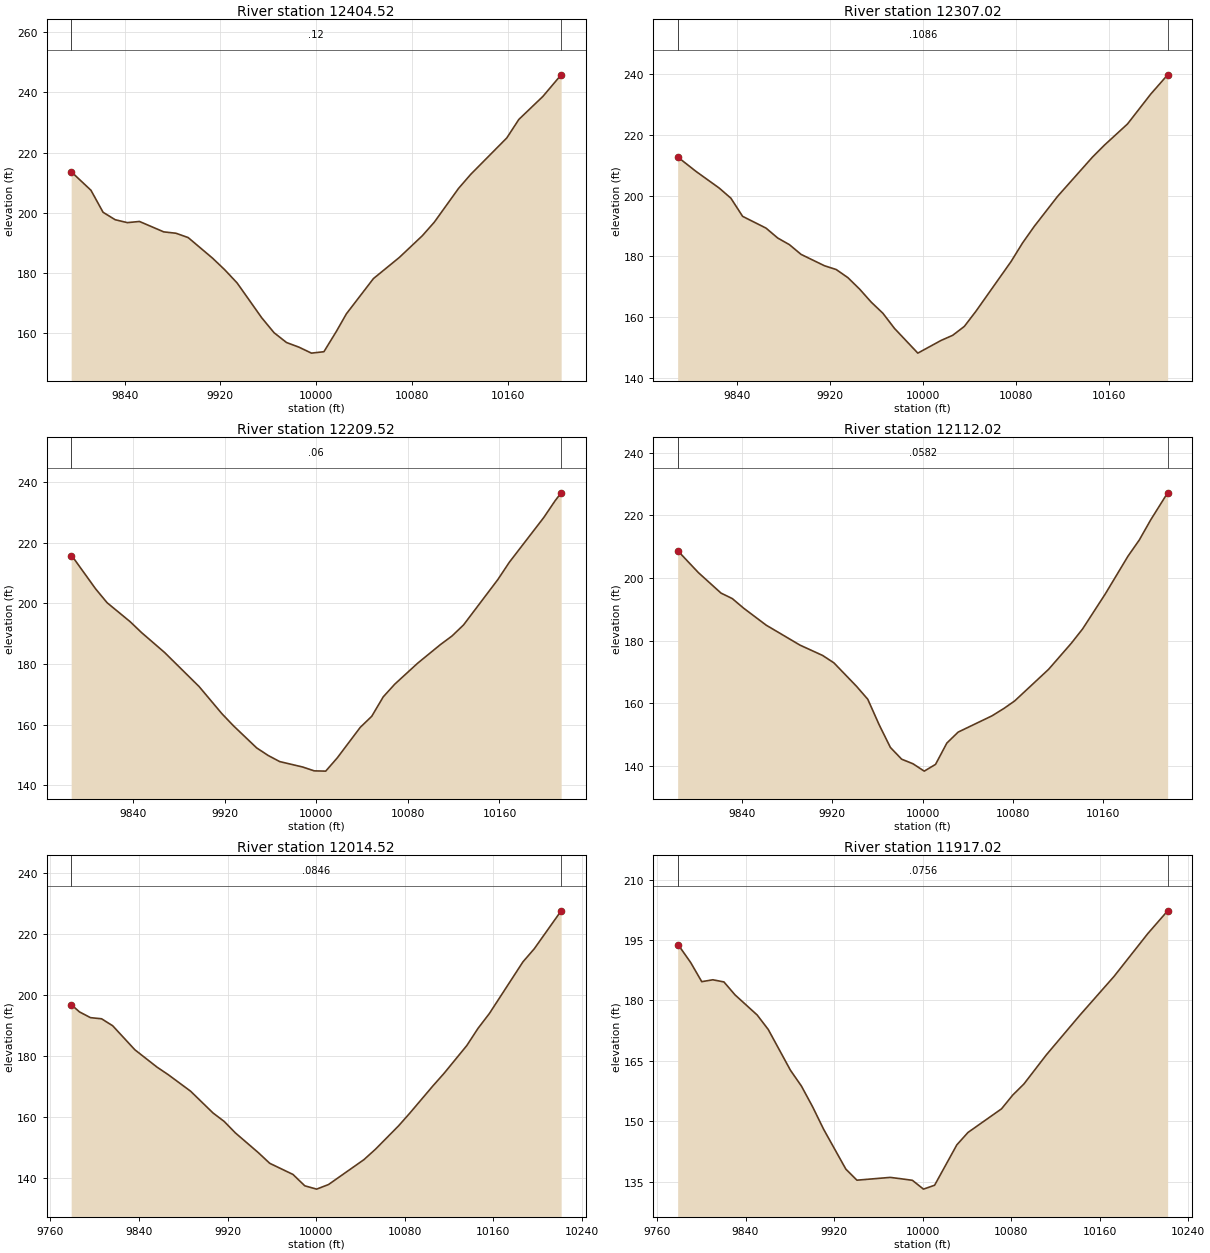
Type RM Length L Ch R = 1 ,12404.52,97.501200,97.501200,97.501200
XS GIS Cut Line= 6
915808.691831701839825.710456348915938.473707462839849.258273616
916039.005303604 839876.70793327 916079.35213992839885.714886375
916146.683792425839895.910990873 916210.21293113839901.849315837
#Sta/Elev= 30
9795.292213.63639811.825 207.4569821.963200.13419832.101197.66639842.239196.7027
9852.377197.08659872.654  193.639882.857193.1758 9893.06191.73419913.465184.8771
9923.667181.01589933.933176.66079954.533165.07139964.833 160.115 9975.21156.8659
9985.631 155.3139996.052153.336910006.47153.805910016.88160.560410025.24166.3943
10047.83178.1039 10069.5185.139610088.61192.312110098.73196.870410118.95208.0726
10129.07212.718410159.28 224.85410169.32230.989610189.41238.636510204.69245.8187
#Mann= 3 , 0 , 0
9795.292    0.12       09795.292    0.12       010204.69    0.12       0
#XS Ineff= 2 , 0
       0                               0
Bank Sta=9795.292,10204.69
Exp/Cntr=0.3,0.1

Type RM Length L Ch R = 1 ,12307.02,97.501200,97.501200,97.501200
XS GIS Cut Line= 6
915779.471917486839942.883059255915943.615742214839961.065564097
915988.145231771 839962.88664427915990.145229646839962.883729009
916026.967065859839963.943513908916199.466457925839975.367627915
#Sta/Elev= 30
9789.285 212.7389804.909208.02979825.031202.50299835.092199.16519845.153193.1957
9865.276189.32589875.337186.06779885.398183.88169895.459180.67289915.581176.9347
9925.643 175.6999935.704 173.0229945.765169.26469955.819164.93949965.827161.2985
9975.835156.29139995.852148.181210015.86152.360310025.87154.047910035.87156.9779
10045.89161.996210075.95178.268510085.98184.4672   10096189.893410116.04199.7665
10146.11212.708510156.13216.553110176.17223.583410196.22233.446510210.71239.7649
#Mann= 3 , 0 , 0
9789.285  0.1086       09789.285  0.1086       010210.71  0.1086       0
#XS Ineff= 2 , 0
       0                               0
Bank Sta=9789.285,10210.71
Exp/Cntr=0.3,0.1

Type RM Length L Ch R = 1 ,12209.52,97.501300,97.501300,97.501300
XS GIS Cut Line= 6
915773.711009504  840040.8933451915908.015283848840051.786129937
915987.688720275840060.354351483916046.744243776840066.011542066
916114.552540898840068.264093468916200.230946436840066.962181812
#Sta/Elev= 30
9786.122215.68059787.415215.33019807.481204.77339817.514 200.2039837.579193.9677
9847.612190.34989867.678183.79639897.776172.56989917.842163.55439927.892159.5889
9948.007152.33819958.065149.83769968.122147.81959988.237146.02049998.294144.7535
10008.34144.665210018.39149.026710038.48159.098810048.53162.761810058.57169.1724
10068.59173.3421 10088.6 180.26610108.61186.444110118.61189.248710128.62192.8718
10158.62207.868510168.62213.559210198.63228.283410208.63 233.87410213.86236.4572
#Mann= 3 , 0 , 0
9786.122    0.06       09786.122    0.06       010213.86    0.06       0
#XS Ineff= 2 , 0
       0                               0
Bank Sta=9786.122,10213.86
Exp/Cntr=0.3,0.1

Type RM Length L Ch R = 1 ,12112.02,97.501200,97.501200,97.501200
XS GIS Cut Line= 6
915756.585005668840155.329475373915972.576171522840156.771988251
915974.576170326840156.774175248916019.150051862840156.668431777
916079.560555314840152.876928732916189.931680764840142.219707932
#Sta/Elev= 30
9783.004208.79229801.419 201.751 9821.42195.2331 9831.42193.4776 9841.42190.4269
9861.421184.99699891.421178.61459911.422175.32549921.422 172.9619941.423165.4855
9951.423161.33289961.423153.25029971.423145.97189981.423142.21069991.424140.7584
10001.42 138.40510011.42140.559310021.42147.353210031.42150.853310061.46156.0613
10072.21158.466110081.49160.805910111.57170.900710131.66179.219110141.71183.8152
 10161.8194.984710181.89207.025310191.94212.212310201.99218.609710216.99227.2357
#Mann= 3 , 0 , 0
9783.004  0.0582       09783.004  0.0582       010216.99  0.0582       0
#XS Ineff= 2 , 0
       0                               0
Bank Sta=9783.004,10216.99
Exp/Cntr=0.3,0.1

Type RM Length L Ch R = 1 ,12014.52,97.501200,97.501200,97.501200
XS GIS Cut Line= 6
915777.588470041840288.116306395915859.710094721840282.401064369
915925.198185647840272.668556345915965.127628257840262.014109487
916070.196269334840225.166840009916208.992884921840198.547805139
#Sta/Elev= 30
9778.704196.82449786.133194.42649796.158192.51949806.182192.14989816.206189.8613
9836.254181.97999856.303176.27719866.372173.81719886.592168.38759906.811161.2586
9916.921158.46789927.031154.70789947.726148.24029958.076144.72849979.086141.0673
 9989.75137.343510000.43136.253810011.15137.754510043.16145.923510053.62149.3567
10074.53157.044810084.88161.302910105.37170.080410115.61174.2734 10136.1183.3719
10146.29189.038310156.43193.847210186.86210.8568   10197 215.10610221.33227.5741
#Mann= 3 , 0 , 0
9778.704  0.0846       09778.704  0.0846       010221.33  0.0846       0
#XS Ineff= 2 , 0
       0                               0
Bank Sta=9778.704,10221.33
Exp/Cntr=0.3,0.1

Type RM Length L Ch R = 1 ,11917.02,127.320400,127.320400,127.320400
XS GIS Cut Line= 6
915803.243620453840355.955457054916002.505945573840344.976207924
916025.250836953840343.485487747916058.291184888 840340.43641861
916128.523765704840330.416812277916242.651899023840308.455837561
#Sta/Elev= 30
9778.639193.76469780.398193.35989790.413 189.4359800.429184.67729810.444 185.147
9820.459184.61559830.474 181.3989850.504176.3926 9860.52172.7898 9880.55162.6655
9890.565158.6906 9900.58153.58239910.595147.95949930.626138.07989940.641135.3372
9970.686136.02979980.704135.68079990.729135.303810000.75133.113810010.79134.0762
10030.88144.117210040.96 147.19910071.26153.072310081.36156.479710091.46159.2362
10111.72166.472910142.27176.414710172.82185.954510203.37196.609410221.35202.2866
#Mann= 3 , 0 , 0
9778.639  0.0756       09778.639  0.0756       010221.35  0.0756       0
#XS Ineff= 2 , 0
       09970.454                       0
Bank Sta=9778.639,10221.35
Exp/Cntr=0.3,0.1

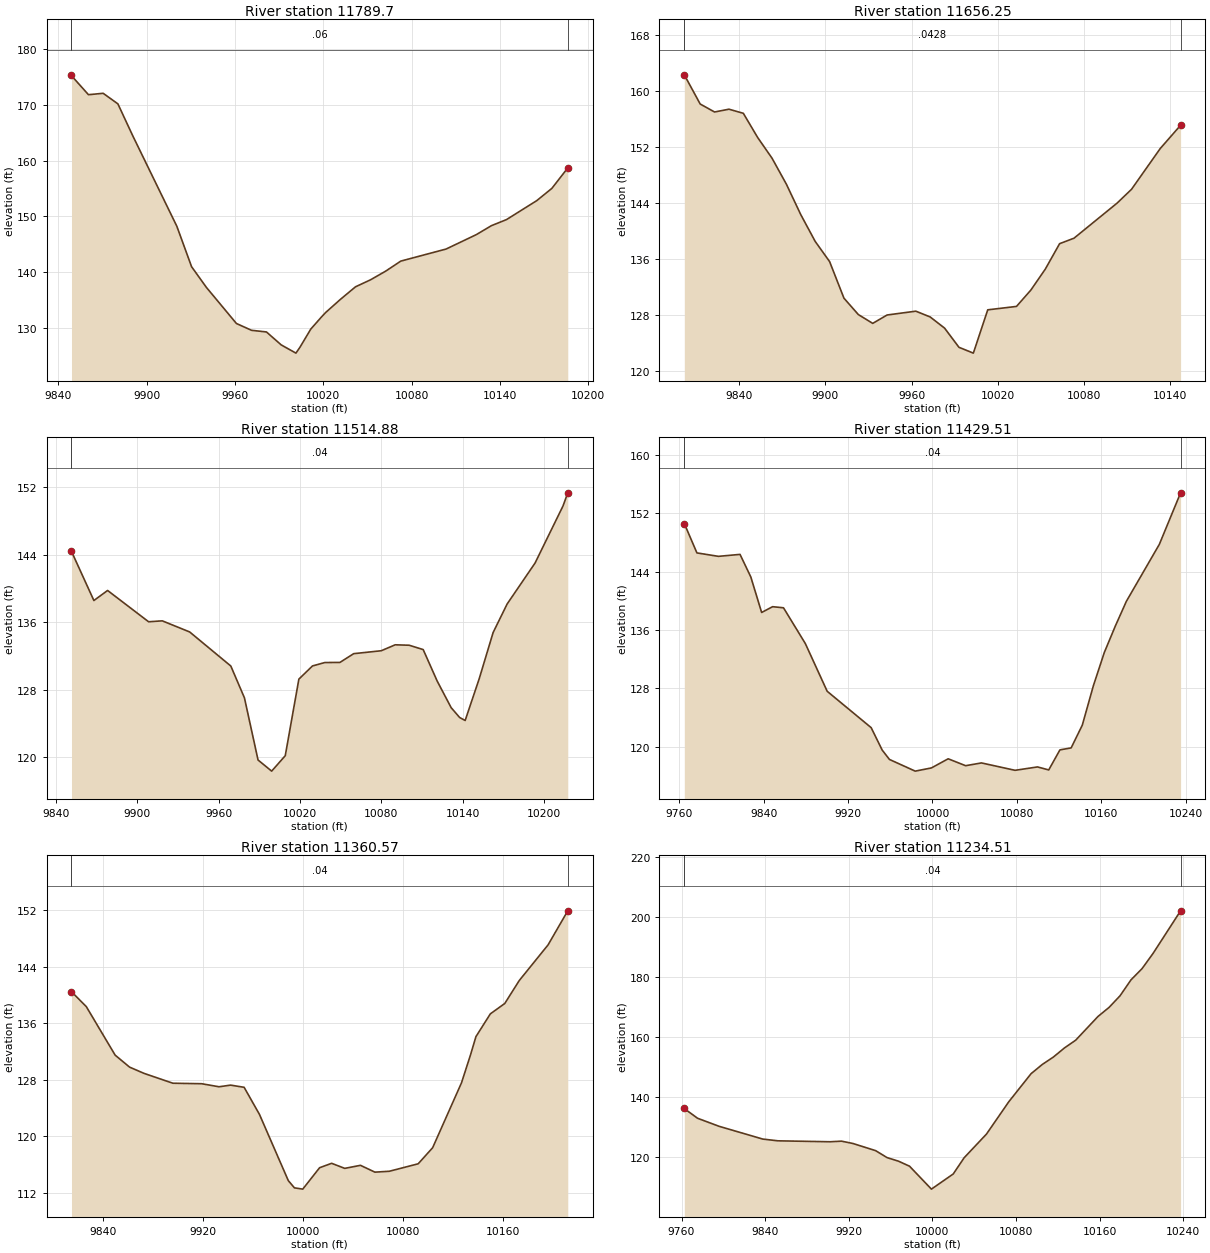
Type RM Length L Ch R = 1 , 11789.7,133.441200,133.441200,133.441200
XS GIS Cut Line= 6
915853.462767779 840456.77000529 915941.62041959 840458.39455532
915986.191188701840467.279279258916007.779137694840467.480263413
916051.683635388840460.031073957916185.520173889840428.830355332
#Sta/Elev= 30
9848.857175.36679850.394174.75639860.396171.80989870.399172.05759880.401170.1666
9890.403164.50589920.456148.24989930.479141.00689940.558137.29669960.934130.8426
9971.187129.61939981.368129.3224 9991.39127.004110001.39125.530910004.17126.6003
10011.49129.8372   10019132.078610021.64132.814610031.78135.191810041.92137.4129
10052.11138.662710062.37140.209810072.64142.008310103.45144.169810123.98146.7522
10134.25148.355210144.52149.447410165.06152.838210175.32155.031710186.13158.6934
#Mann= 3 , 0 , 0
9848.857    0.06       09848.857    0.06       010186.13    0.06       0
#XS Ineff= 2 , 0
       09957.758                       0
Bank Sta=9848.857,10186.13
Exp/Cntr=0.3,0.1

Type RM Length L Ch R = 1 ,11656.25,141.375500,141.375500,141.375500
XS GIS Cut Line= 2
915883.949829717840578.097072219916229.153871901840565.172691197
#Sta/Elev= 30
9801.859162.27369812.917158.10269822.924156.96389832.931157.36329842.938156.7768
9852.945153.31219862.952150.35199872.959146.62869882.966142.28249892.973138.4714
 9902.98135.59679912.987 130.3629922.994128.02319933.001126.76369943.008 127.961
9963.022128.50789973.029127.67779983.036126.08359993.043 123.34510003.05122.5139
10013.06128.699410033.07129.186410043.08131.523110053.08134.500610063.09138.1522
 10073.1138.931910103.12143.949910113.13145.915710133.14151.7462 10147.3155.0696
#Mann= 3 , 0 , 0
9801.859  0.0428       09801.859  0.0428       0 10147.3  0.0428       0
#XS Ineff= 2 , 0
       09959.576                       0
Bank Sta=9801.859,10147.3
Exp/Cntr=0.3,0.1

Type RM Length L Ch R = 1 ,11514.88,85.369000,85.369000,85.369000
XS GIS Cut Line= 6
915888.661470103840685.645000397915965.890785457840696.201728785
916007.076949753840702.514731123  916074.0704639840696.644405099
916117.375871784840688.629012336916248.360192731840655.370640793
#Sta/Elev= 30
9851.535 144.3889868.062138.56729878.178139.75719908.425 136.0489918.507136.1575
9938.703134.84279969.053 130.8059979.108127.03249989.146119.66749999.184118.3481
10009.22120.177210019.26129.2529 10029.3130.8141 10038.4131.217410049.52131.2293
10059.69132.267510080.03132.614910090.31133.318110100.63133.267210110.95132.7524
10121.26129.026810131.58125.869110137.83124.7055 10141.9124.349310152.22129.2724
10162.53  134.7710172.85  138.1510193.48143.012310214.12149.785110217.59151.3293
#Mann= 3 , 0 , 0
9851.535    0.04       09851.535    0.04       010217.59    0.04       0
#XS Ineff= 2 , 0
       0                               0
Bank Sta=9851.535,10217.59
Exp/Cntr=0.3,0.1

Type RM Length L Ch R = 1 ,11429.51,68.941700,68.941700,68.941700
XS GIS Cut Line= 6
915823.305748738840843.358357632915891.488888512840828.935668273
915960.557212253840810.289075266916080.862549369840774.515608982
916182.453480359840737.920768185916274.256590996840710.303893102
#Sta/Elev= 30
9764.702150.57119776.655146.54929797.098146.0785 9817.54146.34669827.761143.2605
9838.031138.39589848.389139.18889858.747139.03829879.463 134.1449900.179127.6115
9941.888122.63469952.326119.56869959.246118.28229983.642116.6852    9999117.1206
10014.92118.372710031.45117.428710046.47117.807410078.36116.795710099.62117.2593
10110.25116.847810120.88119.593110131.51119.862510142.09 122.97710152.53128.3426
10162.97 132.92510173.42136.542510183.86139.918310215.19 147.734 10235.3154.7716
#Mann= 3 , 0 , 0
9764.702    0.04       09764.702    0.04       0 10235.3    0.04       0
#XS Ineff= 2 , 0
       0                10015.37       0
Bank Sta=9764.702,10235.3
Exp/Cntr=0.3,0.1

Type RM Length L Ch R = 1 ,11360.57,126.060800,126.060800,126.060800
XS GIS Cut Line= 2
915924.737915984840933.619832475916268.634491078840736.356117668
#Sta/Elev= 30
9815.019140.4609 9826.85 138.3559849.907131.49279861.435129.79869872.963128.9158
 9896.02127.52219919.077127.45129932.832127.02169942.134127.2536 9952.93126.9469
 9965.19123.11629988.247113.74759993.126112.73339999.775112.550710013.22 115.574
10022.83116.200910033.32115.485310045.89115.914710057.42114.951110068.95115.0766
   10092116.133210103.53118.401310126.59127.580510133.81131.540410138.12134.1104
10149.64 137.32910161.17138.7987 10172.7142.032910195.76147.083310211.48151.8945
#Mann= 3 , 0 , 0
9815.019    0.04       09815.019    0.04       010211.48    0.04       0
#XS Ineff= 2 , 0
       0                10053.96       0
Bank Sta=9815.019,10211.48
Exp/Cntr=0.3,0.1

Type RM Length L Ch R = 1 ,11234.51,97.501200,97.501200,97.501200
XS GIS Cut Line= 6
915942.672433278841009.620338391916022.350675741840987.418229334
916138.549965978840938.988053465916195.811079482840921.553089042
916315.142953192840877.121219881 916390.08268876840852.671244153
#Sta/Elev= 30
 9762.67136.46339765.064135.60329775.348132.99469795.915130.31649837.734126.0623
9852.175125.47999902.121125.16439913.012125.36549923.903124.59569945.685122.2015
9956.575119.89239967.466118.70719978.085117.02439999.022109.389510019.89114.4391
10030.34119.848610051.67127.720910073.01 138.48410094.35147.846510105.02150.9013
10115.69153.384910126.36156.440810137.03159.006110158.37166.9099 10168.9 169.907
10179.41173.774110189.93179.101810200.45182.819210210.97187.877710237.35202.0865
#Mann= 3 , 0 , 0
 9762.67    0.04       0 9762.67    0.04       010237.35    0.04       0
#XS Ineff= 2 , 0
       0                               0
Bank Sta=9762.67,10237.35
Exp/Cntr=0.3,0.1

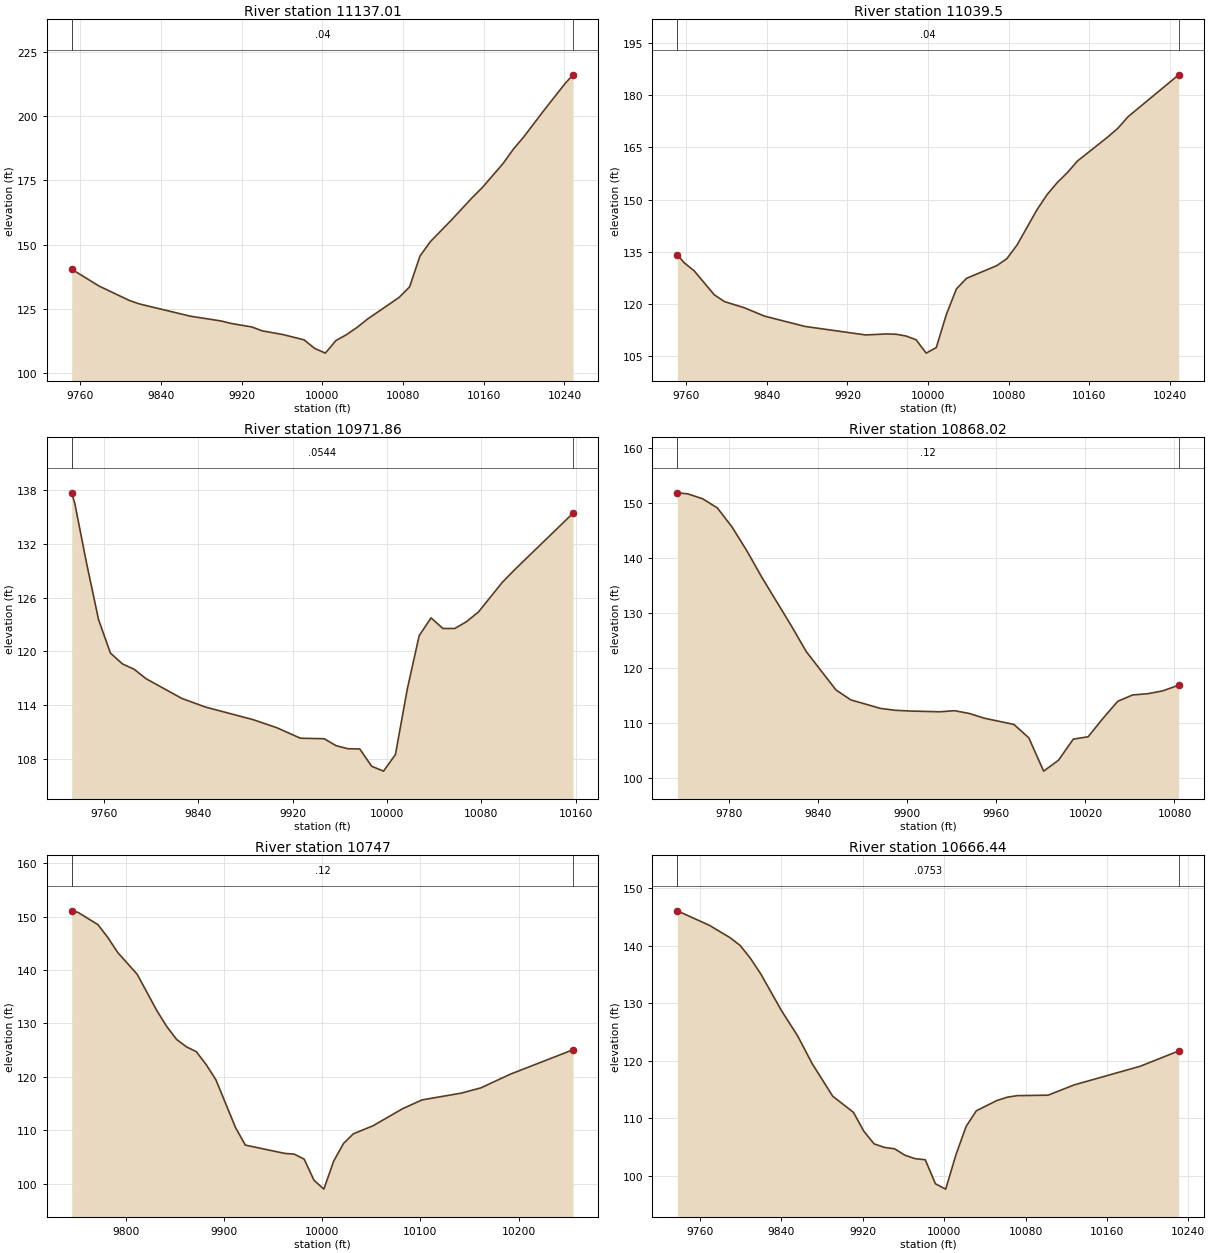
Type RM Length L Ch R = 1 ,11137.01,97.501200,97.501200,97.501200
XS GIS Cut Line= 6
915948.074529934841066.816507771916055.030639831841055.130351569
916128.577141576841042.539034889916167.413318044  841032.5630515
916272.455657729841000.096124621916432.439790479840961.090542164
#Sta/Elev= 30
9751.536140.43069778.621133.8944  9808.8128.27219818.859126.92039869.243122.1706
9899.679120.32249909.825119.34389930.116117.99349940.376116.49389961.025115.0386
9981.833112.99649992.367109.663810002.93107.833810013.48112.730510024.04115.0303
10034.47117.852310044.87121.099910076.06129.473910086.44133.559810096.73145.5297
10107.02151.135110127.61159.407810148.19168.100110158.49172.133910179.07181.4722
10189.37187.095410199.66191.851810220.24202.445310240.83212.691210248.49215.9485
#Mann= 3 , 0 , 0
9751.536    0.04       09751.536    0.04       010248.49    0.04       0
#XS Ineff= 2 , 0
       0                               0
Bank Sta=9751.536,10248.49
Exp/Cntr=0.3,0.1

Type RM Length L Ch R = 1 , 11039.5,67.649600,67.649600,67.649600
XS GIS Cut Line= 6
915968.354671344841106.162519058916049.735416642 841108.66843483
916150.610047691 841118.69139162916188.164835503841119.875056701
916360.098836696841108.659389439916465.117954344841099.258040063
#Sta/Elev= 30
9750.965134.23239757.614131.89399767.619129.57049787.628122.68839797.633120.7411
9817.642118.94079837.675116.54289877.872113.59499938.148111.15059958.158111.4365
9968.163111.35959978.174110.84559988.187109.77099998.201 105.93710008.23107.5384
10018.26117.057310028.28124.3861 10038.3127.396410068.37131.050910078.39133.0616
10088.41136.930810108.46147.166210118.48151.4795 10128.5154.905310138.52157.7529
10148.56161.080810178.68167.970610188.72170.483310198.76173.772910249.07185.7967
#Mann= 3 , 0 , 0
9750.965    0.04       09750.965    0.04       010249.07    0.04       0
#XS Ineff= 2 , 0
       09959.581                       0
Bank Sta=9750.965,10249.07
Exp/Cntr=0.3,0.1

Type RM Length L Ch R = 1 ,10971.86,103.830100,103.830100,103.830100
XS GIS Cut Line= 2
915942.386429602841152.844271986916364.597863287841203.728423389
#Sta/Elev= 30
9732.651 137.6729735.284136.47039745.356129.75929755.428123.52839765.501119.8054
9775.573 118.6079785.646117.99819795.718116.94819825.935114.7603 9846.08113.7891
9886.369112.39139906.514111.49269926.659110.31589946.803110.25869956.876109.4875
9966.948109.1437 9977.02109.11939987.093107.18859997.165106.646710007.24108.4945
10017.31115.794310027.38121.748910037.45 123.73210047.53122.5488 10057.6122.5488
10067.67 123.31810077.74124.400810097.89127.688410107.96129.046810157.92135.4039
#Mann= 3 , 0 , 0
9732.651  0.0544       09732.651  0.0544       010157.92  0.0544       0
#XS Ineff= 2 , 0
       09937.458                       0
Bank Sta=9732.651,10157.92
Exp/Cntr=0.3,0.1

Type RM Length L Ch R = 1 ,10868.02,121.024000,121.024000,121.024000
XS GIS Cut Line= 2
915878.086352503841256.012669307916216.032855484841253.299428099
#Sta/Elev= 30
9744.894151.78379751.808 151.6019761.808150.72329771.808 149.0549781.809145.5631
9791.809141.22539801.809136.4675 9821.81127.5999 9831.81122.95499851.811115.9978
9861.811114.19299881.812112.64779891.812112.30269901.813112.16889921.813112.0338
9931.814112.22879941.814  111.729951.814 110.8659971.815109.73379981.815107.3071
9991.815101.257710001.82103.234310011.82107.070610021.82 107.49410031.82110.8451
10041.82113.943810051.82115.089410061.82 115.30810071.82115.805310082.85116.8561
#Mann= 3 , 0 , 0
9744.894    0.12       09744.894    0.12       010082.85    0.12       0
#XS Ineff= 2 , 0
       0                               0
Bank Sta=9744.894,10082.85
Exp/Cntr=0.3,0.1

Type RM Length L Ch R = 1 ,   10747,80.559600,80.559600,80.559600
XS GIS Cut Line= 6
915898.447196014841352.666664516 916038.89311739841364.196017158
916135.395795599841365.838978292916170.070074213841368.794480831
916247.876592142 841370.45256811916408.849450778841378.572897323
#Sta/Elev= 30
9744.383151.08769750.958150.77889771.025148.51359781.059146.13529791.093143.3249
 9811.16139.19589831.227132.37749841.261129.42019851.295126.99829861.328125.6175
9871.362124.70819881.395122.31439891.409119.43649911.412110.48979921.414107.2004
 9961.42105.65219971.421105.49919981.423104.57019991.453100.6114 10001.598.95091
10011.53104.207110021.55107.501510031.55109.315410051.56 110.81210081.56113.9938
10101.58115.664110141.63116.936110161.65 117.92110191.69120.487310255.62125.0636
#Mann= 3 , 0 , 0
9744.383    0.12       09744.383    0.12       010255.62    0.12       0
#XS Ineff= 2 , 0
       09965.995                       0
Bank Sta=9744.383,10255.62
Exp/Cntr=0.3,0.1

Type RM Length L Ch R = 1 ,10666.44,125.797100,125.797100,125.797100
XS GIS Cut Line= 5
915903.543476376841411.737937533916021.170058295841425.848636675
 916101.38396488841439.804070304916182.267402576841447.734661025
916392.547488637841422.994289781
#Sta/Elev= 30
9737.713146.05219769.395143.51579789.538141.3892 9799.61140.01029809.681137.7681
9819.753135.08549839.896128.77689856.182124.2626 9870.22119.51699890.521113.8407
9910.821111.05189920.971107.79589931.121105.57689941.235104.96059951.283104.7194
9961.331103.61319971.379 103.0079981.426102.81589991.47498.6376910001.5297.71216
10011.57 103.66110021.62108.606610031.69111.325110051.83113.0976 10061.9113.6707
10071.97113.952510102.18114.029110127.86115.8172 10192.8119.0566 10230.6  121.71
#Mann= 3 , 0 , 0
9737.713  0.0753       09737.713  0.0753       0 10230.6  0.0753       0
#XS Ineff= 2 , 0
       09963.872                       0
Bank Sta=9737.713,10230.6
Exp/Cntr=0.3,0.1

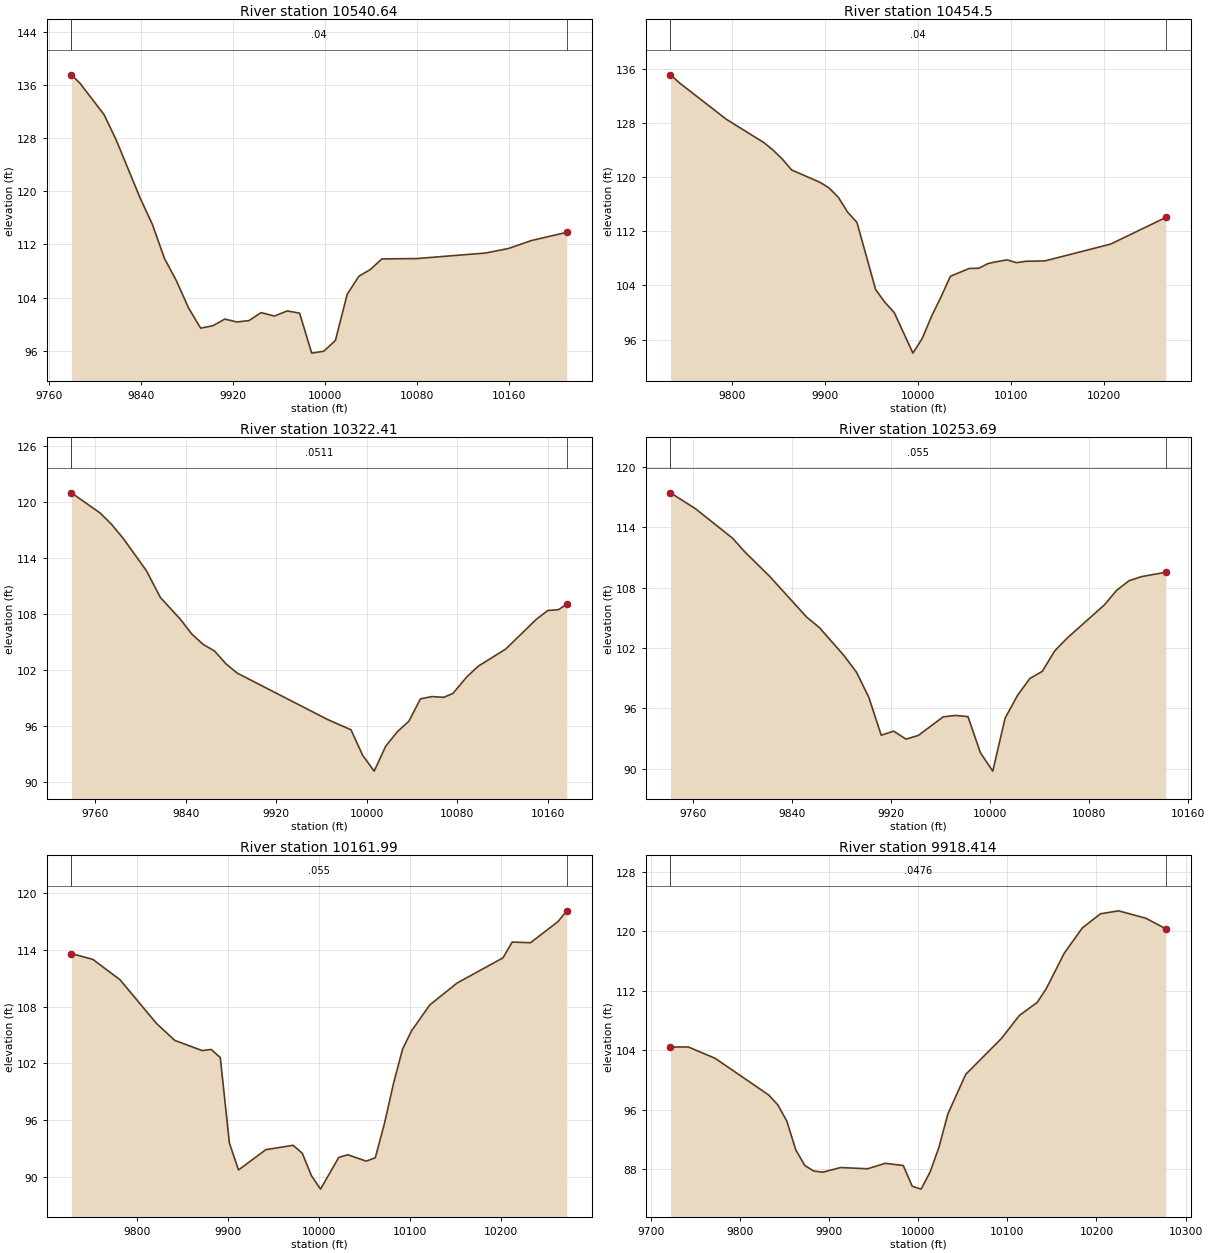
Type RM Length L Ch R = 1 ,10540.64,86.146900,86.146900,86.146900
XS GIS Cut Line= 6
915908.052097244841486.551134544916067.121516903841537.974593263
916098.435978031841553.198223063  916142.0110376841563.400470218
916215.504113792841566.949959021916325.567753974841560.845430992
#Sta/Elev= 30
9779.834137.50099787.136136.26529808.155131.53259818.664127.74899839.683118.9363
9850.193 115.0329860.702109.90679871.212106.51039881.722102.42979892.23199.40827
9902.74199.75948 9913.25100.7677 9923.76100.33659934.269100.53919944.779101.7452
9956.384101.22569967.489101.9962 9978.27101.66189988.80595.649769999.21195.92746
10009.4597.5587410019.64104.488410029.77107.200610039.81108.223910049.85109.8189
10079.91109.867910139.97110.7005   10160111.384810180.03112.588210210.64113.8158
#Mann= 3 , 0 , 0
9779.834    0.04       09779.834    0.04       010210.64    0.04       0
#XS Ineff= 2 , 0
       09971.237                       0
Bank Sta=9779.834,10210.64
Exp/Cntr=0.3,0.1

Type RM Length L Ch R = 1 , 10454.5,132.088200,132.088200,132.088200
XS GIS Cut Line= 6
915824.862729494 841650.43004449915946.573237254841648.382843878
916089.593353635841639.401599778916107.197228046841638.711048973
916236.540094081841617.032998412916353.840496823841602.006314968
#Sta/Elev= 30
 9733.97135.09879744.109133.85219794.116128.52149834.122125.10999844.123123.9898
9854.125122.65729864.142121.05039894.201119.2539 9904.22118.4105 9914.24117.0265
 9924.26114.82319934.279113.30439954.319103.40299964.339101.50619974.35899.98653
9994.39894.0129510004.4196.1928610014.4299.4646610024.53102.304910034.67 105.367
10054.95106.513310065.09106.543510075.23107.246910085.37 107.53910095.51107.7826
10105.65107.365310115.79107.573710136.07107.6251 10206.7110.108110266.03114.0412
#Mann= 3 , 0 , 0
 9733.97    0.04       0 9733.97    0.04       010266.03    0.04       0
#XS Ineff= 2 , 0
       09966.326                       0
Bank Sta=9733.97,10266.03
Exp/Cntr=0.3,0.1

Type RM Length L Ch R = 1 ,10322.41,68.718800,68.718800,68.718800
XS GIS Cut Line= 5
 915909.76654201841732.375162689 916015.11495481841749.518902414
916129.680485344841749.987812236916217.127523478841730.683821895
916341.367742615841703.420085264
#Sta/Elev= 30
9738.959121.00169764.524118.82289774.656117.59679784.787116.1098 9805.05 112.695
9817.559109.79579835.445107.42579845.576 105.8399855.578104.74879865.578104.0422
9875.578102.67859885.578101.67349965.70796.691149986.18995.602189996.42992.88194
10006.6791.1688910016.9193.8432610027.1595.3903910037.3996.5192210047.6398.91681
10057.8799.1612610068.1199.0766210076.3399.4961410088.59  101.2710098.82102.4249
10122.98104.250610150.01 107.43510160.25108.388910169.64108.474710177.01109.0615
#Mann= 3 , 0 , 0
9738.959  0.0511       09738.959  0.0511       010177.01  0.0511       0
#XS Ineff= 2 , 0
       0                               0
Bank Sta=9738.959,10177.01
Exp/Cntr=0.3,0.1

Type RM Length L Ch R = 1 ,10253.69,91.696700,91.696700,91.696700
XS GIS Cut Line= 2
915944.915273076841803.998636433916344.687334895841798.466889524
#Sta/Elev= 30
9742.113117.42239762.199115.85239792.202112.91449802.203111.54149822.205109.1165
9852.208105.04569862.209104.04229882.211101.23779892.21299.602019902.21397.09279
9912.21493.328529922.21493.736069932.21592.941669942.21693.311529962.21895.15411
9972.21995.29681 9982.2295.176719992.22191.6009910002.2289.7601610012.2295.03086
10022.2297.2922810032.2398.9728810042.2399.6840310052.23101.708610062.23102.9771
10092.23106.271110102.23107.731210112.23 108.68310122.23109.092510141.92109.5281
#Mann= 3 , 0 , 0
9742.113   0.055       09742.113   0.055       010141.92   0.055       0
#XS Ineff= 2 , 0
       09976.123                       0
Bank Sta=9742.113,10141.92
Exp/Cntr=0.3,0.1

Type RM Length L Ch R = 1 ,10161.99,243.579700,243.579700,243.579700
XS GIS Cut Line= 6
915911.573022825841890.410495724916095.696971359841883.494868534
916255.738382026841892.987916628916297.168063711841893.372285972
916360.523746811841889.295064262916454.483880675841877.360335013
#Sta/Elev= 30
9727.888 113.6269751.332113.01989781.353110.85119821.381106.22029841.395104.4317
9871.416103.35269881.424103.47089891.431102.61099901.43893.556799911.44590.70078
9941.48392.849629971.52193.317039981.53492.467699991.546 90.098510001.5688.66934
10021.6192.0334710031.6392.3131710051.6891.6354110061.7191.9897210071.7395.59381
10081.7499.8642310091.74 103.51110101.74105.468110121.75108.202310151.81110.5207
10202.06113.178710212.14114.846910232.31114.780910262.55117.025210272.11118.1591
#Mann= 3 , 0 , 0
9727.888   0.055       09727.888   0.055       010272.11   0.055       0
#XS Ineff= 2 , 0
       09961.868        10050.67       0
Bank Sta=9727.888,10272.11
Exp/Cntr=0.3,0.1

Type RM Length L Ch R = 1 ,9918.414,186.269700,186.269700,186.269700
XS GIS Cut Line= 6
915925.295748078842100.205567695916135.544573476842124.314830662
 916192.65321153842127.848995656916274.281571866842124.852876565
916329.132923579842119.932930526916477.187698076 842095.16540697
#Sta/Elev= 30
9722.138 104.4119741.971104.43159772.168102.90449832.56197.942659842.62796.61714
9852.69294.435189862.75890.556459872.82388.470099882.88987.718719892.95487.56343
9913.08588.190659943.23888.025689963.27688.758699983.31588.46545 9993.3385.66877
10003.3485.2831210013.3487.5683610023.3590.9178810033.36 95.415610053.37100.7332
10093.47105.577510113.55108.667710133.66 110.44110143.77112.287210163.97117.0669
10184.17120.4553 10204.5122.358810224.83122.761110255.32121.769910277.88120.3468
#Mann= 3 , 0 , 0
9722.138  0.0476       09722.138  0.0476       010277.88  0.0476       0
#XS Ineff= 2 , 0
       09915.509                       0
Bank Sta=9722.138,10277.88
Exp/Cntr=0.3,0.1

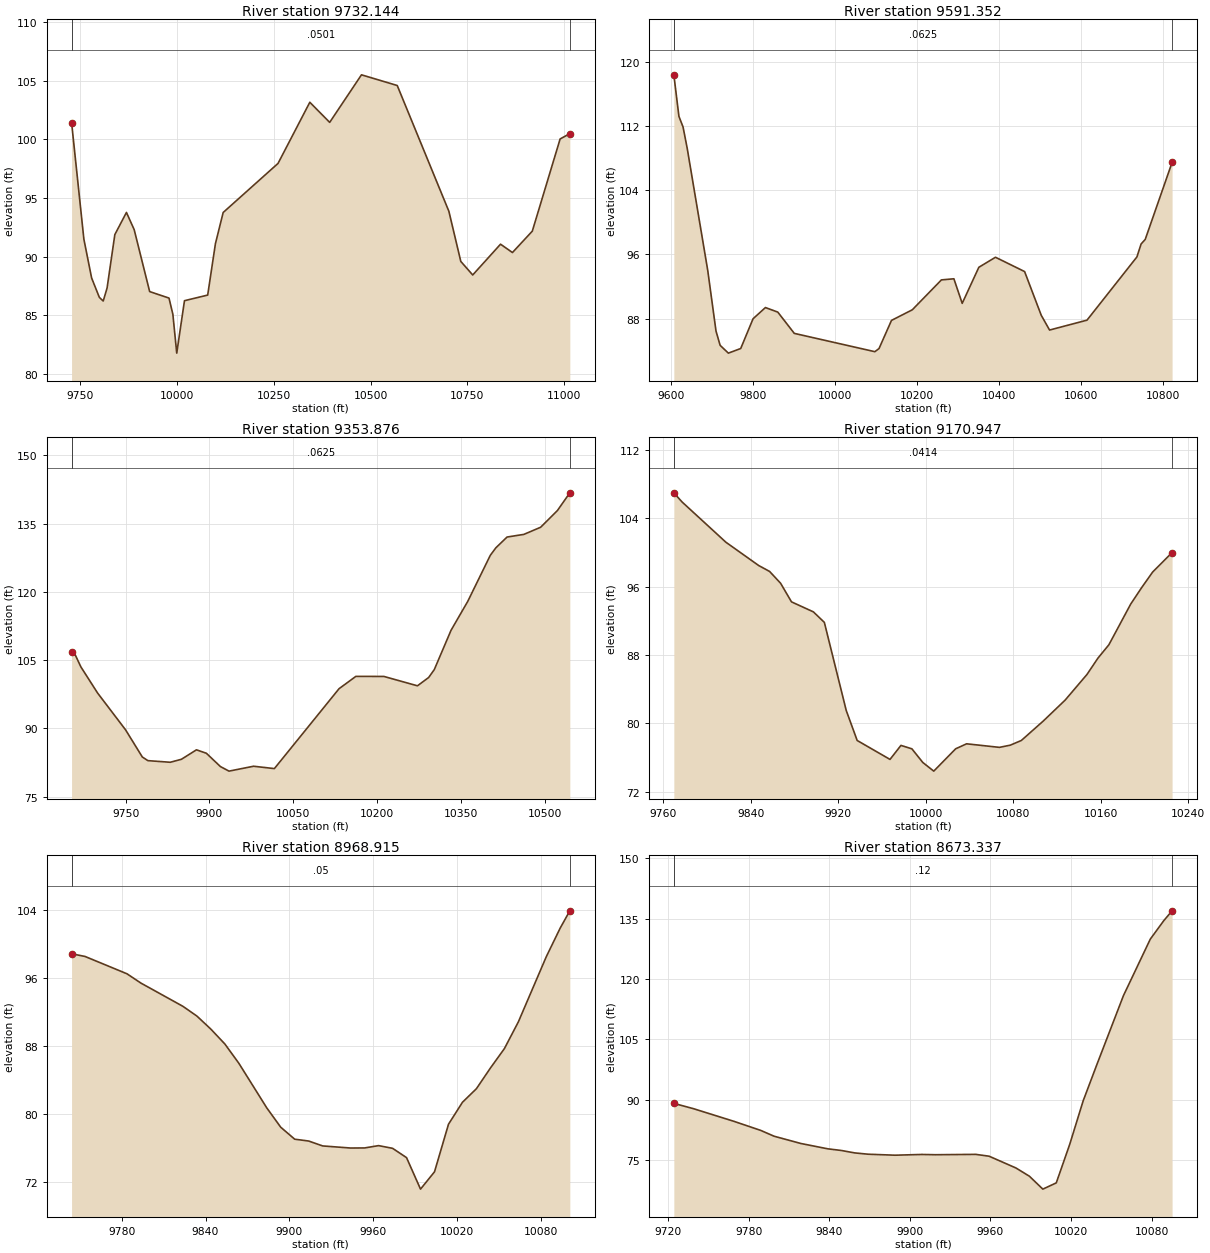
Type RM Length L Ch R = 1 ,9732.144,140.792100,140.792100,140.792100
XS GIS Cut Line= 3
915883.196427792842300.620008513916347.307987839842305.888629019
917149.430801988842118.382998288
#Sta/Elev= 30
 9727.05101.43279758.85691.482279778.857  88.1759798.85886.519779808.85986.21087
 9818.8687.324319838.86191.874179868.86393.763339888.86492.297899928.86787.01514
 9978.8786.46078 9988.8785.078149998.87181.7667810018.8786.2375910078.8886.71769
10098.8891.1006210118.8893.7586710260.7197.9449110342.87103.158510394.21 101.444
10476.37105.4985 10568.8104.5887 10702.393.8620110733.1189.5877610763.9288.43089
10835.8191.0559710866.61 90.344610917.9692.1702110989.85100.029411014.94100.4849
#Mann= 3 , 0 , 0
 9727.05  0.0501       0 9727.05  0.0501       011014.94  0.0501       0
#XS Ineff= 2 , 0
       09872.713        10060.12       0
Bank Sta=9727.05,11014.94
Exp/Cntr=0.3,0.1

Type RM Length L Ch R = 1 ,9591.352,237.475800,237.475800,237.475800
XS GIS Cut Line= 4
915862.654626042842397.161252201916153.364540428842426.649780706
 916288.99822095842386.502211273917059.587051958842252.497581631
#Sta/Elev= 30
9606.156118.42989618.565113.24169628.616 111.9189638.668109.28299688.924 93.9922
9709.02786.438649719.07884.653489739.18183.677489769.33584.253789799.48987.97104
9829.643 89.36799859.796 88.80019900.06386.1430910096.6583.85795 10106.884.24859
10137.25 87.7643   1018889.0867810259.0592.82105 10289.592.96033 10309.889.89112
 10350.494.39667   1039195.6491110462.0593.8622810502.6588.4051310522.9586.56069
 10614.387.7939510736.1195.6902310746.2697.3005810756.4197.8798310821.96107.4927
#Mann= 3 , 0 , 0
9606.156  0.0625       09606.156  0.0625       010821.96  0.0625       0
#XS Ineff= 2 , 0
       09836.825        10021.02       0
Bank Sta=9606.156,10821.96
Exp/Cntr=0.3,0.1

Type RM Length L Ch R = 1 ,9353.876,182.929400,182.929400,182.929400
XS GIS Cut Line= 4
 915898.37322098842488.498739034916121.897526532842496.094225153
 916269.46697095842630.642836273916737.131901532842665.365058482
#Sta/Elev= 30
9653.051 106.7859659.682106.15569669.688103.54279699.70597.781639749.73489.70668
9779.75183.732949789.75782.93124 9829.7882.575049849.79183.232969876.70485.30946
9894.43684.555159919.60781.630019935.03380.627459978.97681.7018110016.2381.18306
10132.0998.7483710162.17101.449110212.31101.440210272.4899.3786310292.53101.2059
10302.56102.925910332.64 111.58210362.72117.974210402.83128.036110412.86129.7039
10432.92132.0743   10463132.656510493.08 134.22510523.16 137.90310545.36141.7929
#Mann= 3 , 0 , 0
9653.051  0.0625       09653.051  0.0625       010545.36  0.0625       0
#XS Ineff= 2 , 0
       09978.201        10067.75       0
Bank Sta=9653.051,10545.36
Exp/Cntr=0.3,0.1

Type RM Length L Ch R = 1 ,9170.947,202.031600,202.031600,202.031600
XS GIS Cut Line= 2
 915837.46742523842649.635096961 916292.77542005842666.859372693
#Sta/Elev= 30
9769.581106.98439777.119105.91199817.148101.20579847.16998.474049857.176 97.7793
9867.18396.40199 9877.1994.218499897.20593.046929907.212 91.81859927.22681.50392
9937.23377.993589967.25575.777649977.26277.416339987.26977.015729997.27675.41462
10007.2874.40559 10027.377.02008 10037.377.6034110067.3377.1875510077.3377.44849
10087.3477.9923710107.3680.2644610127.3782.7147410147.3885.7231110157.3987.63238
 10167.489.1958110187.4193.9731410197.4295.8980510207.4397.7106310225.2199.99389
#Mann= 3 , 0 , 0
9769.581  0.0414       09769.581  0.0414       010225.21  0.0414       0
#XS Ineff= 2 , 0
       0                               0
Bank Sta=9769.581,10225.21
Exp/Cntr=0.3,0.1

Type RM Length L Ch R = 1 ,8968.915,295.578200,295.578200,295.578200
XS GIS Cut Line= 2
915885.361487814842778.861177839916241.815008927842783.392239611
#Sta/Elev= 30
9744.14698.804039753.78698.485959783.78896.449399793.78995.354179823.79192.62884
9833.79291.484469843.79389.947139853.79488.205759863.79585.941649883.79680.69409
9893.797 78.41959903.79877.012379913.79976.79625  9923.876.221489943.80175.97556
9953.80275.985119963.80376.258669973.80475.941049983.804 74.84639993.80571.14581
10003.81  73.18110013.8178.7683110023.8181.3521110033.8182.9487210043.8185.37558
10053.81 87.657810063.8190.8026710083.8198.4669410093.81101.844610100.63103.8488
#Mann= 3 , 0 , 0
9744.146    0.05       09744.146    0.05       010100.63    0.05       0
#XS Ineff= 2 , 0
       0                               0
Bank Sta=9744.146,10100.63
Exp/Cntr=0.3,0.1

Type RM Length L Ch R = 1 ,8673.337,382.396000,382.396000,382.396000
XS GIS Cut Line= 2
915930.356426888842958.567461898916301.211404001842968.277994181
#Sta/Elev= 26
9724.255 89.09959738.903 87.78159768.91484.65001 9788.9282.389529798.92480.93884
9818.93179.129449838.93877.808559848.94177.402239858.94476.794419868.94876.47116
9888.95576.226439908.96276.409769918.96576.344219948.97576.432349958.97975.97838
9978.985 73.05169988.98971.003789998.99267.79879   10009 69.3506   1001978.91036
   1002989.7061110039.0198.5469910059.01115.864410079.02129.909510089.02 134.477
10095.24136.9332
#Mann= 3 , 0 , 0
9724.255    0.12       09724.255    0.12       010095.24    0.12       0
#XS Ineff= 2 , 0
       0                               0
Bank Sta=9724.255,10095.24
Exp/Cntr=0.3,0.1