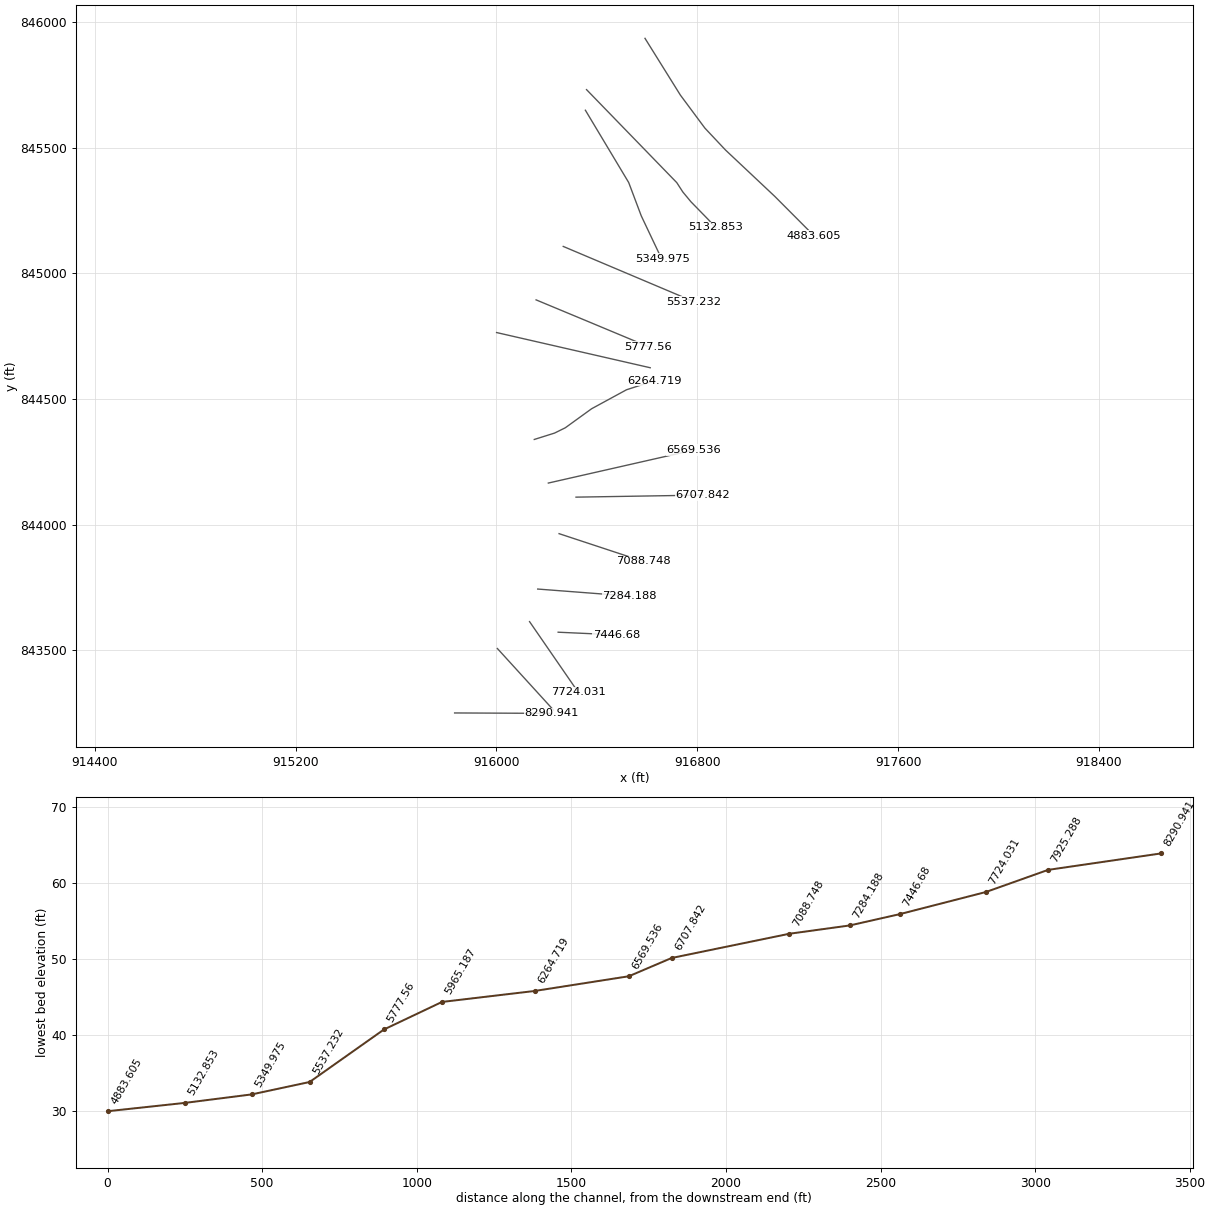
HEC-RAS study 16794_ras.prj: 16794

--- 16794_ras.g01 (geometry) --- (continued)

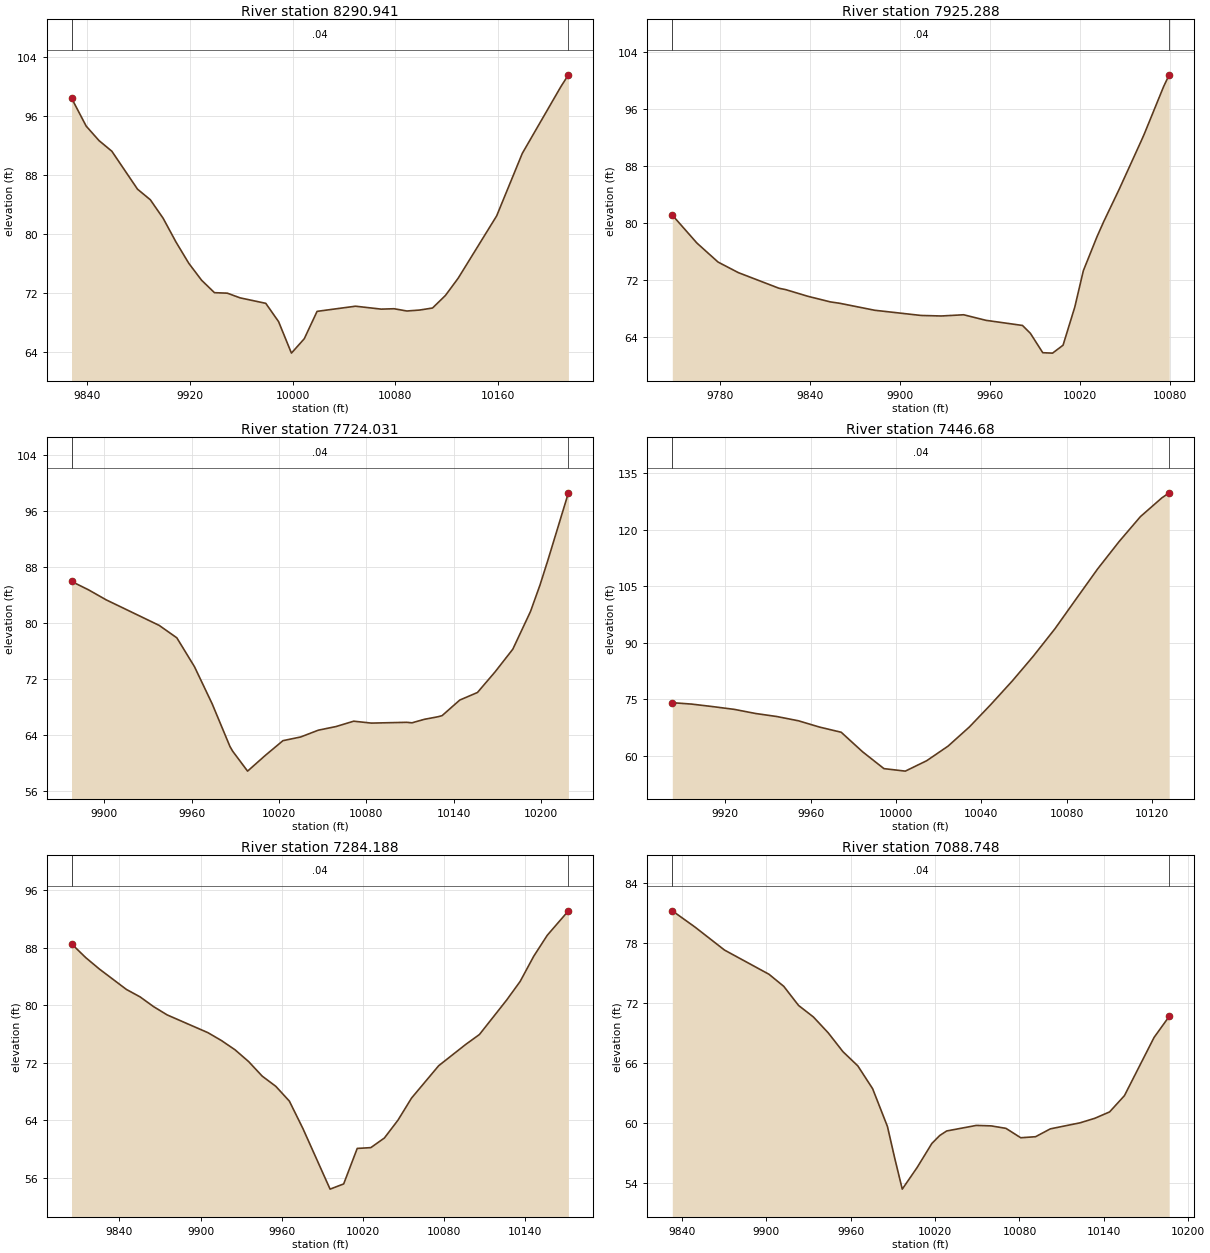
Type RM Length L Ch R = 1 ,8290.941,365.653000,365.653000,365.653000
XS GIS Cut Line= 2
915833.551133095 843251.25264976916220.935240002 843249.56102116
#Sta/Elev= 30
9827.60798.401219839.05694.606849849.05792.650819859.05791.209029879.05786.08075
9889.05784.646419899.05782.139469909.05778.929559919.05776.048229929.05773.75464
9939.057 72.07829949.05772.011459959.05871.377039979.05870.636779989.05868.15998
9999.05863.9011710009.0665.8458410019.0669.5510110049.0670.2482110069.0669.85214
10079.0669.9060910089.0669.5991810099.0669.7293710109.0670.0036510119.0671.69028
10129.0674.0368710159.0682.4668610179.0690.9255710209.0699.92963   10215101.5456
#Mann= 3 , 0 , 0
9827.607    0.04       09827.607    0.04       0   10215    0.04       0
#XS Ineff= 2 , 0
       0                               0
Bank Sta=9827.607,10215
Exp/Cntr=0.3,0.1

Type RM Length L Ch R = 1 ,7925.288,201.257300,201.257300,201.257300
XS GIS Cut Line= 2
916003.937376507843507.549694017916227.475102361843262.695525612
#Sta/Elev= 28
9748.257 81.14029764.66477.21487 9778.79 74.53679792.33173.051779819.41270.85702
9823.99170.658889838.82369.719379853.655 68.93929860.03368.739429883.31967.76051
9914.19667.031649927.73666.956379942.646 67.12819957.47766.348259981.89865.62505
9987.14164.530819995.439 61.793810001.9761.7352810008.9862.84919 10016.868.20163
10022.5273.3277610031.6478.1099510036.0680.2029310046.47 84.7911 10061.3  91.649
10063.14 92.528410076.13  99.236 10079.8100.8597
#Mann= 3 , 0 , 0
9748.257    0.04       09748.257    0.04       0 10079.8    0.04       0
#XS Ineff= 2 , 0
       09923.716                       0
Bank Sta=9748.257,10079.8
Exp/Cntr=0.3,0.1

Type RM Length L Ch R = 1 ,7724.031,277.350800,277.350800,277.350800
XS GIS Cut Line= 2
916132.074956395843614.573884777916326.089591949843333.553430497
#Sta/Elev= 30
9877.40685.92641 9889.0484.733559901.19283.299289937.64779.646469949.79977.86645
9961.951 73.73129974.10268.424029986.25462.361539988.162 61.67039998.40658.82433
10010.5661.0653310022.7163.1765310034.8663.7019210047.0164.6728510059.1665.19233
10071.3265.9581310083.4765.6862410107.7765.7966910111.3765.7258410119.9266.22691
10128.9766.5811910132.0766.7497110144.2368.9785510156.38 70.057910168.53  73.013
10180.6876.2477410192.8381.6296710199.3885.4304110204.9889.0945310218.8998.58416
#Mann= 3 , 0 , 0
9877.406    0.04       09877.406    0.04       010218.89    0.04       0
#XS Ineff= 2 , 0
       0                               0
Bank Sta=9877.406,10218.89
Exp/Cntr=0.3,0.1

Type RM Length L Ch R = 1 , 7446.68,162.492400,162.492400,162.492400
XS GIS Cut Line= 2
916245.987411071843572.440475106 916478.45566539843561.923841432
#Sta/Elev= 26
9895.25674.083569904.27773.707729914.28873.032669924.29872.305979934.30871.20817
9944.31870.399069954.32869.278849964.33967.591929974.34966.240249984.35961.06144
9994.36956.5938110004.38 55.928410014.3958.68884 10024.4 62.556710034.4167.65411
10044.4273.5946710054.4379.8180210059.8983.4516610064.4486.5009410074.4593.68406
10084.46101.657710094.47109.576610104.48 116.79810114.49123.4304 10124.5128.3953
10127.96129.7386
#Mann= 3 , 0 , 0
9895.256    0.04       09895.256    0.04       010127.96    0.04       0
#XS Ineff= 2 , 0
       0                               0
Bank Sta=9895.256,10127.96
Exp/Cntr=0.3,0.1

Type RM Length L Ch R = 1 ,7284.188,195.439900,195.439900,195.439900
XS GIS Cut Line= 2
916164.512509146843744.144583297916530.572263194 843716.15232165
#Sta/Elev= 30
9804.66388.547459815.18186.62486 9825.2185.044889845.26982.196199855.29881.17044
9865.32779.807679875.35678.657649905.444 76.19039915.47375.090159925.502 73.8049
9935.53172.16977 9945.5670.14443 9955.5968.731299965.61966.673699975.64862.85012
9995.70654.4333310005.7455.1573910015.7660.0929310025.7960.2035510035.8261.54097
10045.8564.0205410055.8867.0944210075.9471.59525   10096 74.568210106.03 75.9316
10126.09 80.710510136.1283.3125910146.1486.8125810156.1789.7351310171.7993.13311
#Mann= 3 , 0 , 0
9804.663    0.04       09804.663    0.04       010171.79    0.04       0
#XS Ineff= 2 , 0
       0                               0
Bank Sta=9804.663,10171.79
Exp/Cntr=0.3,0.1

Type RM Length L Ch R = 1 ,7088.748,380.906000,380.906000,380.906000
XS GIS Cut Line= 2
 916249.73908339843964.455497628916585.228355418843854.006394052
#Sta/Elev= 30
9833.24281.253859849.30979.632529870.36577.317089901.94974.892799912.47773.67944
9923.00571.761829933.53370.608749944.06169.017619954.58967.119459965.11765.70119
9975.64463.411059986.17259.621489991.39556.40999  9996.753.3404110007.23 55.5022
10017.76 57.926510023.3758.7222610028.28 59.173810049.3459.7308110059.8759.68405
 10070.459.4357410080.92 58.493510091.4558.5976310101.98 59.386510123.0459.98972
10133.5660.4441710144.0961.0870110154.6262.7156710175.6868.5542710186.4470.66488
#Mann= 3 , 0 , 0
9833.242    0.04       09833.242    0.04       010186.44    0.04       0
#XS Ineff= 2 , 0
       0                10061.61       0
Bank Sta=9833.242,10186.44
Exp/Cntr=0.3,0.1

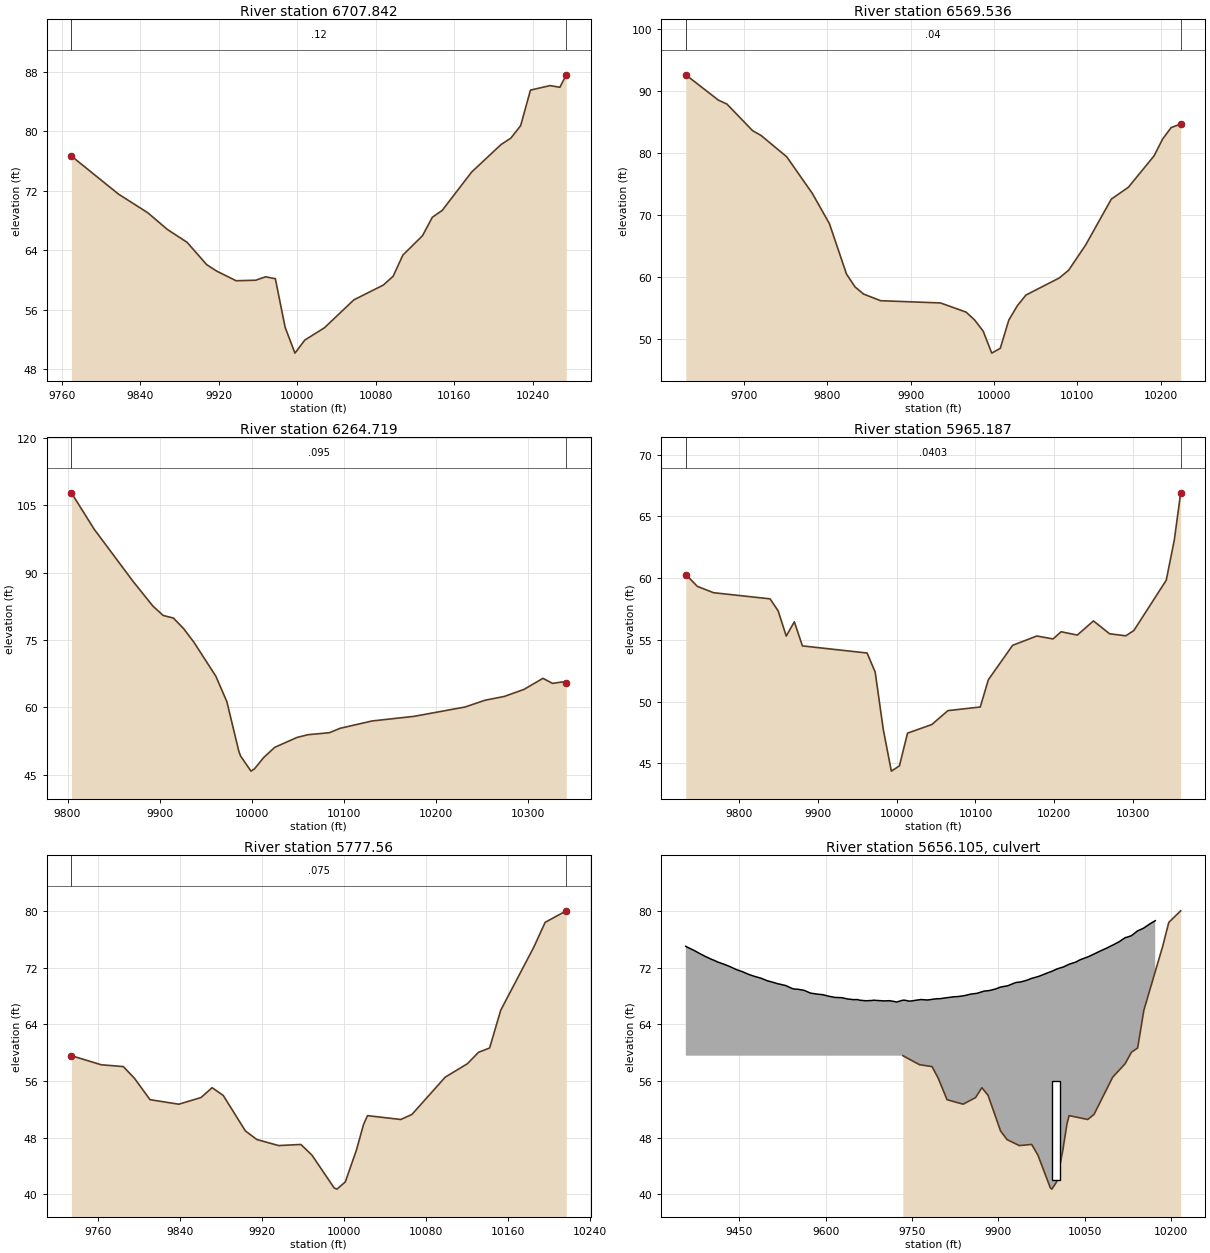
Type RM Length L Ch R = 1 ,6707.842,138.306000,138.306000,138.306000
XS GIS Cut Line= 2
 916317.14018175844109.734002622916821.514225728844117.946561724
#Sta/Elev= 30
9769.62676.642439817.49271.544289847.49669.021059867.49866.774729887.50165.05607
9907.50462.049949917.50561.194849937.508 59.8833 9957.5159.955019967.51260.41458
9977.51360.156139987.51453.610569997.51650.1531210007.5251.9067610027.5253.55785
10057.5257.3131910087.5359.2991610097.53 60.477210107.5363.3392710127.5365.93569
10137.5368.4201610147.5469.3292710177.5474.4850610207.5478.1904910217.5479.04921
10227.5580.7255310237.5585.5083510257.5586.1189510267.55 85.889210274.07  87.565
#Mann= 3 , 0 , 0
9769.626    0.12       09769.626    0.12       010274.07    0.12       0
#XS Ineff= 2 , 0
       0                               0
Bank Sta=9769.626,10274.07
Exp/Cntr=0.3,0.1

Type RM Length L Ch R = 1 ,6569.536,304.816800,304.816800,304.816800
XS GIS Cut Line= 2
916206.880425335844165.808641424 916786.16224863844297.210743661
#Sta/Elev= 30
9629.92792.668019669.01588.586789679.26987.954839710.03183.663749720.28582.87818
9751.04779.44551 9781.81 73.53199802.31868.642169822.82660.51121 9833.0858.43726
9843.33457.283049863.84256.21408 9935.6255.852549966.38254.371529976.63653.10208
 9986.8951.298739997.14547.75344 10007.448.5360310017.6553.0881310027.9155.40792
10038.1657.1220710078.3259.8937910089.4361.1294910109.9465.22114 10140.7 72.6083
10161.2174.5284510191.9779.5879510202.2382.2946210212.4884.1529210223.9384.72513
#Mann= 3 , 0 , 0
9629.927    0.04       09629.927    0.04       010223.93    0.04       0
#XS Ineff= 2 , 0
       0                               0
Bank Sta=9629.927,10223.93
Exp/Cntr=0.3,0.1

Type RM Length L Ch R = 1 ,6264.719,299.532000,299.532000,299.532000
XS GIS Cut Line= 6
916150.923772247844339.216258298916231.786065575844364.625545717
916274.717289182 844385.83194506916379.276115137 844461.34965946
916518.521466207844536.978658973916629.430459775844572.822683524
#Sta/Elev= 30
 9804.24107.77459829.08499.639989871.27488.03896 9892.6782.571579903.82380.47716
9914.97779.89367 9926.1377.531949937.30574.489519961.07266.936749972.98661.29253
9986.07350.179649987.983  49.1539999.189 45.816310003.0746.3412510012.7848.80048
10024.93 51.107510049.0353.3065110061.0753.9248210084.4254.3728210095.9955.35215
 10130.756.9852810176.3458.0142710231.6960.0961810253.0161.5837310274.3362.45241
10295.4864.0017110316.1866.4759810326.5365.3473110336.8865.6607210341.4765.49983
#Mann= 3 , 0 , 0
 9804.24   0.095       0 9804.24   0.095       010341.47   0.095       0
#XS Ineff= 2 , 0
       0                               0
Bank Sta=9804.24,10341.47
Exp/Cntr=0.3,0.1

Type RM Length L Ch R = 1 ,5965.187,187.627300,187.627300,187.627300
XS GIS Cut Line= 2
916000.751291459844764.529372249 916612.87253339844624.493846371
#Sta/Elev= 30
9732.435 60.30069747.05259.342139767.56958.826999839.37758.328929849.63557.35007
9859.89455.314469870.15256.471289880.41154.519159962.47753.941149972.73652.39945
9982.99447.760949993.25244.3755110003.5144.8030110013.7747.4510410044.5448.14748
10065.0649.2755610106.0949.5705910116.3551.7791110147.1354.56483 10177.955.32076
10198.4255.0822710208.6855.6649710229.1955.3948810249.7156.5414410270.2355.49811
10290.74  55.336   1030155.7644510342.0459.8339710352.2963.0836310360.3766.91597
#Mann= 3 , 0 , 0
9732.435  0.0403       09732.435  0.0403       010360.37  0.0403       0
#XS Ineff= 2 , 0
       09955.375        10049.93       0
Bank Sta=9732.435,10360.37
Exp/Cntr=0.3,0.1

Type RM Length L Ch R = 1 , 5777.56,240.327800,240.327800,240.327800
XS GIS Cut Line= 3
916158.216022531844894.445646241916365.645811947844808.254004613
916604.037286137844708.877674928
#Sta/Elev= 30
9734.18959.566949763.194 58.29139784.86758.02843 9795.6856.386429810.92853.36406
9838.99652.728139860.65453.665239871.48355.055969882.31253.96958 9903.9748.95997
9915.17247.745889936.45746.895319958.11547.051859968.94845.543759990.61640.91661
9993.26140.7553710001.4541.7686310012.2846.2438910019.2549.8674510023.1251.11649
10055.6250.5734710066.4651.2813310098.9656.5393410120.6358.4386810131.4660.04694
10142.2960.6524810153.1365.9783810185.6374.9338410196.4678.3639410217.09 79.9901
#Mann= 3 , 0 , 0
9734.189   0.075       09734.189   0.075       010217.09   0.075       0
#XS Ineff= 2 , 0
       0 9962.32                       0
Bank Sta=9734.189,10217.09
Exp/Cntr=0.3,0.1

Type RM Length L Ch R = 2 ,5656.105,,,
Bridge Culvert--1,0,-1,-1, 0
Deck Dist Width WeirC Skew NumUp NumDn MinLoCord MaxHiCord MaxSubmerge Is_Ogee
70.164,100,2.6,0,108,108, , , 0.95, 0, 0,0,,
 9356.85 9358.82 9369.54 9378.77 9380.27 9391.00 9401.72 9406.44 9412.45 9423.17
 9433.90 9434.10 9444.62 9455.35 9461.76 9466.07 9476.80 9487.52 9489.43 9498.25
 9508.97 9517.09 9519.70 9530.42 9541.15 9544.75 9551.87 9562.60 9572.42 9573.33
 9584.05 9594.78 9600.08 9605.50 9616.23 9626.95 9627.74 9637.68 9648.40 9655.41
 9659.13 9669.85 9680.58 9683.07 9691.30 9702.03 9710.73 9712.75 9723.48 9734.20
 9738.39 9744.93 9749.81 9755.66 9765.96 9766.40 9777.13 9787.87 9793.46 9798.60
 9809.34 9820.07 9820.96 9830.80 9841.54 9848.46 9852.27 9863.01 9873.74 9875.96
 9884.48 9895.21 9903.46 9905.95 9916.68 9927.42 9930.96 9938.15 9948.89 9958.46
 9959.62 9970.36 9981.09 9985.96 9991.8310002.5610013.3010013.4610024.0310034.77
10040.9610045.5010056.2410066.9710068.4610077.7110088.4410095.9610099.1810109.91
10120.6510123.4610131.3810142.1210150.9610152.8510163.5910172.88
   74.99   74.89   74.48   74.07   74.00   73.55   73.15   73.00   72.77   72.46
   72.12   72.11   71.71   71.41   71.18   71.03   70.74   70.49   70.43   70.14
   69.90   69.70   69.66   69.46   69.06   68.97   68.93   68.78   68.43   68.40
   68.26   68.17   68.06   67.95   67.78   67.75   67.75   67.57   67.47   67.48
   67.39   67.31   67.35   67.39   67.34   67.29   67.32   67.30   67.14   67.39
   67.38   67.26   67.29   67.37   67.49   67.48   67.42   67.54   67.60   67.60
   67.73   67.84   67.86   67.91   68.04   68.18   68.25   68.36   68.63   68.68
   68.75   68.97   69.23   69.27   69.43   69.79   69.89   69.95   70.18   70.48
   70.50   70.75   71.09   71.25   71.42   71.81   72.08   72.09   72.49   72.76
   73.04   73.19   73.51   73.92   73.98   74.34   74.73   75.05   75.16   75.62
   76.21   76.26   76.48   77.16   77.48   77.56   78.15   78.60
                                                                                
                                                                                
                                                                                
                                                                                
                                                                                
                                                                                
                                                                                
                                                                                
                                                                                
                                                                                
                                                                
 9356.85 9358.82 9369.54 9378.77 9380.27 9391.00 9401.72 9406.44 9412.45 9423.17
 9433.90 9434.10 9444.62 9455.35 9461.76 9466.07 9476.80 9487.52 9489.43 9498.25
 9508.97 9517.09 9519.70 9530.42 9541.15 9544.75 9551.87 9562.60 9572.42 9573.33
 9584.05 9594.78 9600.08 9605.50 9616.23 9626.95 9627.74 9637.68 9648.40 9655.41
 9659.13 9669.85 9680.58 9683.07 9691.30 9702.03 9710.73 9712.75 9723.48 9734.20
 9738.39 9744.93 9749.81 9755.66 9765.96 9766.40 9777.13 9787.87 9793.46 9798.60
 9809.34 9820.07 9820.96 9830.80 9841.54 9848.46 9852.27 9863.01 9873.74 9875.96
 9884.48 9895.21 9903.46 9905.95 9916.68 9927.42 9930.96 9938.15 9948.89 9958.46
 9959.62 9970.36 9981.09 9985.96 9991.8310002.5610013.3010013.4610024.0310034.77
10040.9610045.5010056.2410066.9710068.4610077.7110088.4410095.9610099.1810109.91
10120.6510123.4610131.3810142.1210150.9610152.8510163.5910172.88
   74.99   74.89   74.48   74.07   74.00   73.55   73.15   73.00   72.77   72.46
   72.12   72.11   71.71   71.41   71.18   71.03   70.74   70.49   70.43   70.14
   69.90   69.70   69.66   69.46   69.06   68.97   68.93   68.78   68.43   68.40
   68.26   68.17   68.06   67.95   67.78   67.75   67.75   67.57   67.47   67.48
   67.39   67.31   67.35   67.39   67.34   67.29   67.32   67.30   67.14   67.39
   67.38   67.26   67.29   67.37   67.49   67.48   67.42   67.54   67.60   67.60
   67.73   67.84   67.86   67.91   68.04   68.18   68.25   68.36   68.63   68.68
   68.75   68.97   69.23   69.27   69.43   69.79   69.89   69.95   70.18   70.48
   70.50   70.75   71.09   71.25   71.42   71.81   72.08   72.09   72.49   72.76
   73.04   73.19   73.51   73.92   73.98   74.34   74.73   75.05   75.16   75.62
   76.21   76.26   76.48   77.16   77.48   77.56   78.15   78.60
                                                                                
                                                                                
                                                                                
                                                                                
                                                                                
                                                                                
                                                                                
                                                                                
                                                                                
                                                                                
                                                                
BR Coef=-1 , 0 , 0 ,, 0 ,,,0.8,-1,,0,
WSPro=,,,, 1 ,,,, 0 ,,,, 0 ,,,,-1 ,-1 ,-1 , 0 , 0 , 0 , 0 , 0
Culvert=2,14,14,100,0.013,0.5,1,8,3,42,10000,34,10000,Culvert #1, 0, 70.164
Culvert Bottom n=0.013
BC Design=,, 0 ,, 0 ,,,,,,

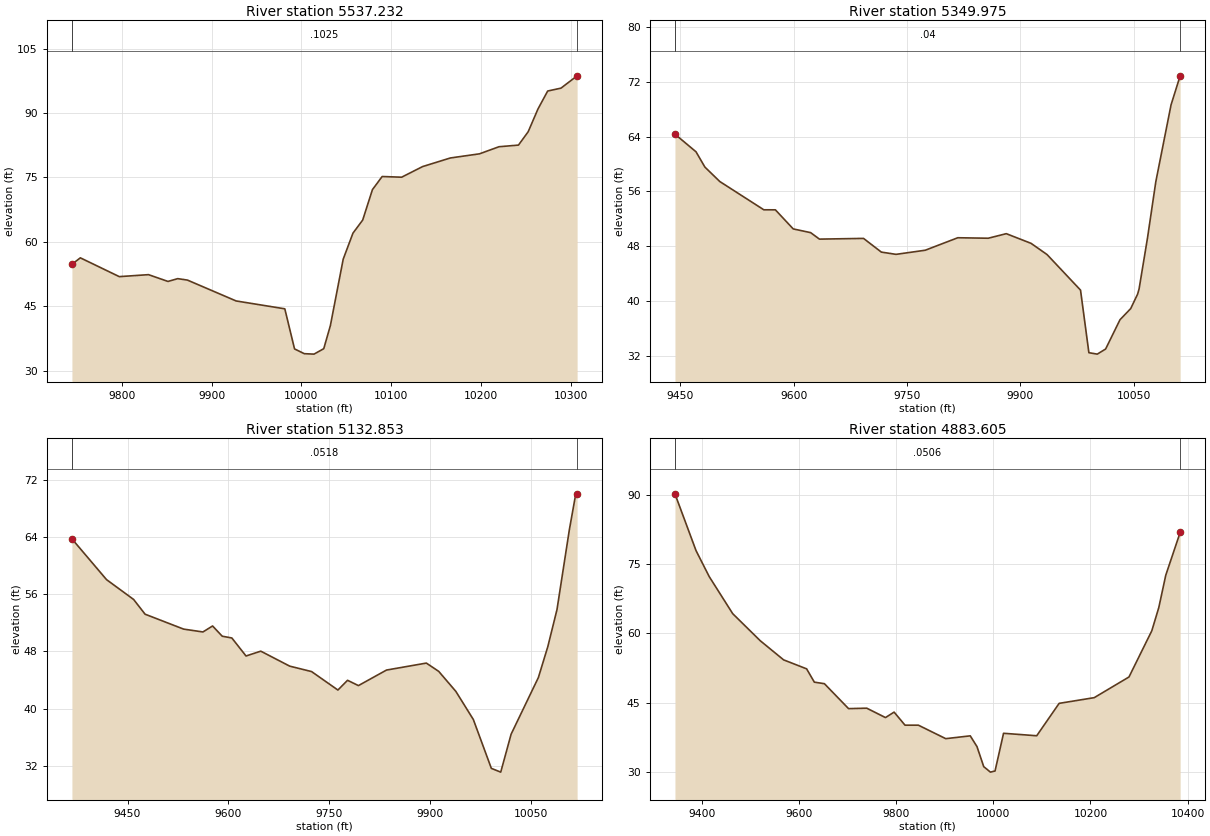
Type RM Length L Ch R = 1 ,5537.232,187.257400,187.257400,187.257400
XS GIS Cut Line= 2
916266.343619789845107.063940822916785.241565028844888.004765027
#Sta/Elev= 30
9744.12354.771749753.51956.271379796.93851.895189829.50252.354929851.21150.77675
9862.06551.42665 9872.9251.090519927.19346.231699981.46644.40226 9992.3235.06646
10003.1833.9582910014.0333.8533610024.8835.1190610032.2640.4857110046.5955.97563
10057.4562.01766 10068.365.0656810079.1672.1495910090.0175.2049910111.7275.04494
10135.1177.5175610165.9979.5193510198.5680.4874610220.27 82.138210241.98 82.5202
10252.8385.6388510263.6990.9124610274.5495.1069510289.3895.7793310307.37 98.6466
#Mann= 3 , 0 , 0
9744.123  0.1025       09744.123  0.1025       010307.37  0.1025       0
#XS Ineff= 2 , 0
       09971.176                       0
Bank Sta=9744.123,10307.37
Exp/Cntr=0.3,0.1

Type RM Length L Ch R = 1 ,5349.975,217.121100,217.121100,217.121100
XS GIS Cut Line= 6
916354.490188977 845648.93729471916527.098202216 845361.28503182
 916577.09239207845228.778573308916651.870703428845071.189797176
916655.970048867845066.309902117916661.960308053845057.631313284
#Sta/Elev= 30
9442.92264.372759470.83861.78941  9482.559.565459502.21857.452789560.52453.31714
9575.79853.311779599.39450.522979622.447 49.97939634.109 49.0309 9692.4249.13608
9716.00547.13347 9735.4446.804899774.05547.40561 9817.1749.232149857.428 49.1611
9881.298 49.82759914.08548.413619935.26346.774589979.53841.577969990.60732.43055
10001.6832.2214110012.7432.9675210031.7637.2461510045.9538.8804610055.0940.99752
10057.0241.7509610068.0949.1534510079.1657.4234410099.31 68.652610111.3672.89852
#Mann= 3 , 0 , 0
9442.922    0.04       09442.922    0.04       010111.36    0.04       0
#XS Ineff= 2 , 0
       0                               0
Bank Sta=9442.922,10111.36
Exp/Cntr=0.3,0.1

Type RM Length L Ch R = 1 ,5132.853,249.248100,249.248100,249.248100
XS GIS Cut Line= 6
916359.099480472845730.876337821916718.821957232845360.633779046
916742.606931241845323.843646586916775.151475401845284.615597535
916844.480456947845213.772434333916872.820296436845182.892396464
#Sta/Elev= 30
9367.20963.742529418.728 58.03849459.05855.262119476.12953.200179533.531 51.1123
9562.23250.715589576.58251.551959590.93350.120379605.28349.87223 9626.3747.35216
9648.33448.028199691.38645.932469723.96945.170999763.13842.587629777.488 43.9507
9793.68243.20989 9835.5145.384319894.80546.359289913.224 45.19819938.726 42.3967
9964.71338.470469991.54131.6286310005.5231.1006710020.9936.4109710061.5944.34192
10075.6148.6634610089.2453.8336510107.6865.0203710116.3869.5884610119.2470.04486
#Mann= 3 , 0 , 0
9367.209  0.0518       09367.209  0.0518       010119.24  0.0518       0
#XS Ineff= 2 , 0
       09946.171                       0
Bank Sta=9367.209,10119.24
Exp/Cntr=0.3,0.1

Type RM Length L Ch R = 1 ,4883.605,249.248100,249.248100,249.248100
XS GIS Cut Line= 6
916591.994278395845934.910666461916732.927296234845709.162367345
916830.640945776845577.766990319916912.816727856845490.537047963
917109.503822219845305.748214669917265.619871626845149.317956623
#Sta/Elev= 30
 9344.0690.208469387.50377.920589414.68772.297569463.03664.288369519.68658.44098
9567.941 54.28969615.27352.352159631.21149.468639651.91949.140779701.71443.74245
9739.14643.840369777.73141.808799795.52442.989919818.02340.163519845.55540.16491
9901.87637.247549952.40337.857629966.27535.528419980.14731.198589993.88830.00932
10003.4630.2541910020.9938.4100310089.3137.8755510135.5344.88428 10207.846.11824
10279.3850.5896110326.4260.5865610340.7965.6012610355.1772.60736 10384.881.85484
#Mann= 3 , 0 , 0
 9344.06  0.0506       0 9344.06  0.0506       0 10384.8  0.0506       0
#XS Ineff= 2 , 0
       09944.724        10026.38       0
Bank Sta=9344.06,10384.8
Exp/Cntr=0.3,0.1