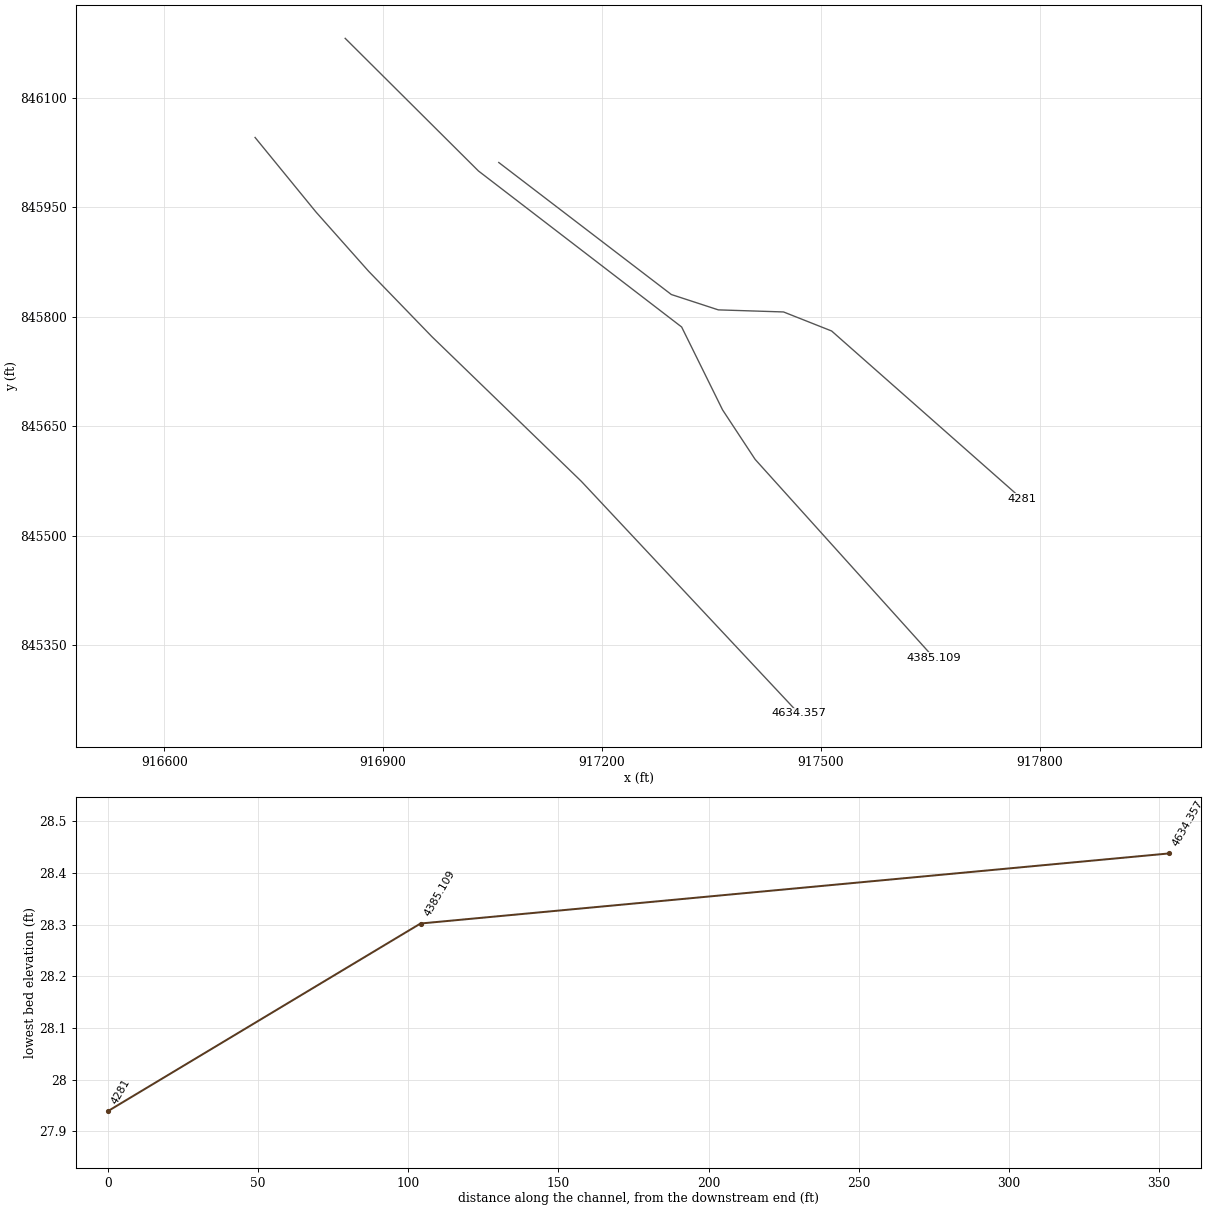
HEC-RAS study 16794_ras.prj: 16794

--- 16794_ras.g01 (geometry) --- (continued)

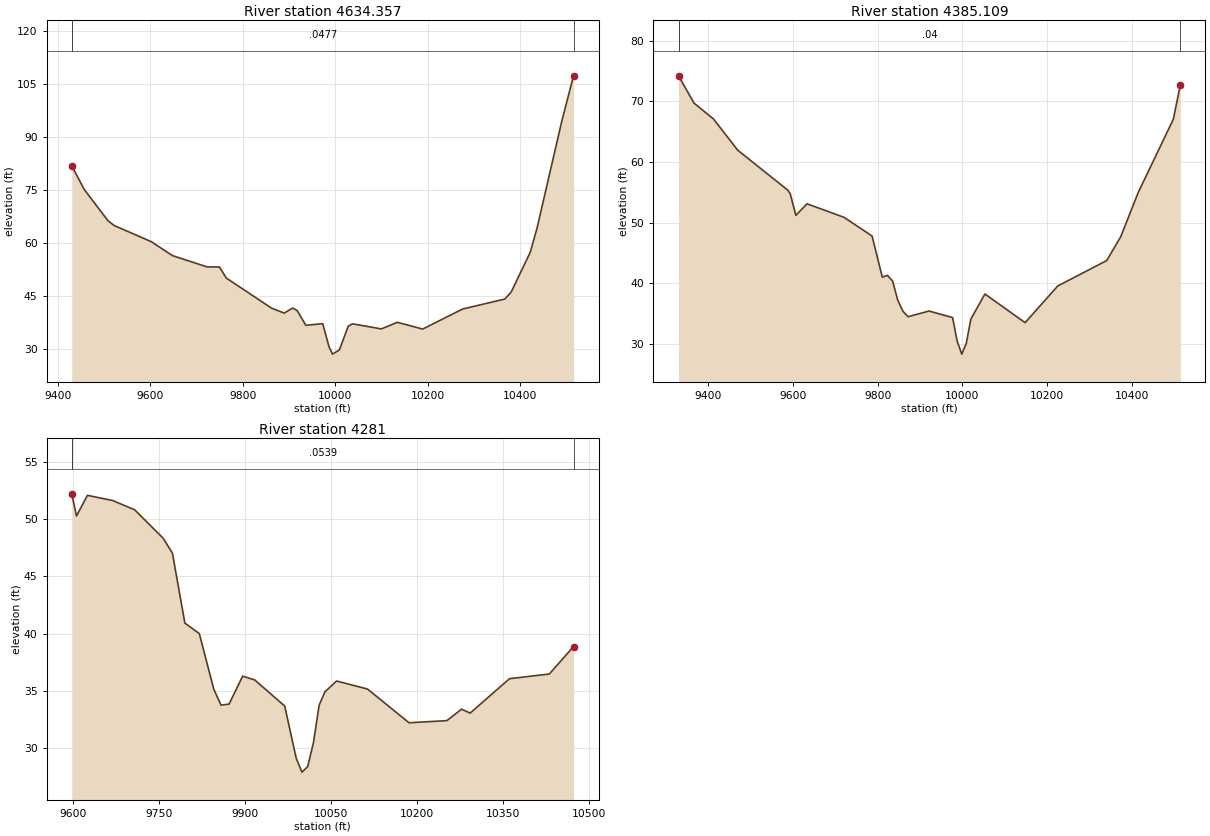
Type RM Length L Ch R = 1 ,4634.357,249.248100,249.248100,249.248100
XS GIS Cut Line= 6
916724.504349697846045.907861113916807.952206815845943.764465797
916880.085091314845862.559161815916966.771838152845772.997476596
917171.616973655845574.672639536917469.371943628845256.794072165
#Sta/Elev= 30
9429.66281.830779456.24175.200269507.90766.269389520.92164.93138  9602.360.27793
9647.47356.369289722.45953.172789749.147 53.1504 9764.2149.993629861.71241.50033
9889.44740.068219907.40941.501999917.18340.843049936.27636.604889972.654 37.0801
9986.52130.48391 9994.0128.4378810008.68 29.607710028.0236.3569310037.2237.03018
10099.5735.5885210134.2737.4577310189.0335.5393510275.3141.2173610366.9744.05889
10380.6646.0523810421.7257.27342 10436.464.0724310490.1694.5094910515.53107.3309
#Mann= 3 , 0 , 0
9429.662  0.0477       09429.662  0.0477       010515.53  0.0477       0
#XS Ineff= 2 , 0
       09967.544        10052.78       0
Bank Sta=9429.662,10515.53
Exp/Cntr=0.3,0.1

Type RM Length L Ch R = 1 ,4385.109,104.109100,104.109100,104.109100
XS GIS Cut Line= 6
916847.961927589846181.736324153917030.591390221845999.975315106
917308.991877042845786.211706036917365.080893974845672.613364597
917409.679666713 845604.82459561917654.388646767845333.210724876
#Sta/Elev= 30
9330.56874.179519367.11569.679039413.01967.063099470.17561.919069588.31255.33146
9594.11654.704649607.28151.174679633.612 53.08499720.95650.848529787.02247.76764
9811.19140.991299823.27541.28912 9835.3640.362079847.44437.225169859.52835.39952
9871.61334.469279921.35535.406099976.97934.324929987.77330.419769998.56828.30228
10009.2530.0843910019.9834.0752110053.1738.2161310147.9933.4889710224.9239.53299
10340.4243.7267710373.5347.6634710414.5554.9139210497.4967.0193110514.0272.66964
#Mann= 3 , 0 , 0
9330.568    0.04       09330.568    0.04       010514.02    0.04       0
#XS Ineff= 2 , 0
       09957.701        10044.08       0
Bank Sta=9330.568,10514.02
Exp/Cntr=0.3,0.1

Type RM Length L Ch R = 1 ,    4281,0.000000,0.000000,0.000000
XS GIS Cut Line= 6
917058.416759058846011.600822314917294.873584504845830.710690873
917359.245635973 845809.67625066917448.582522764 845806.82734499
917514.481832426845780.746569373917775.367336298845550.496075442
#Sta/Elev= 30
9598.58952.193579606.87750.260079625.91152.06123 9669.8351.610389708.20250.80128
9757.57648.343079774.03547.028279795.73640.926779820.91740.013949846.09835.16926
9858.689 33.78189872.78433.863899896.43536.303399917.47535.973539969.77833.69872
9989.77929.15627 9999.7827.9391510009.7828.4131710019.7930.4842610029.8233.77704
10039.8734.9363410060.1835.8815410114.0935.17982 10186.532.2399810252.37 32.4266
10277.93 33.425710293.0333.0851110361.5936.0829910431.0136.4919510473.1738.88418
#Mann= 3 , 0 , 0
9598.589  0.0539       09598.589  0.0539       010473.17  0.0539       0
#XS Ineff= 2 , 0
       09938.951        10102.35       0
Bank Sta=9598.589,10473.17
Exp/Cntr=0.3,0.1